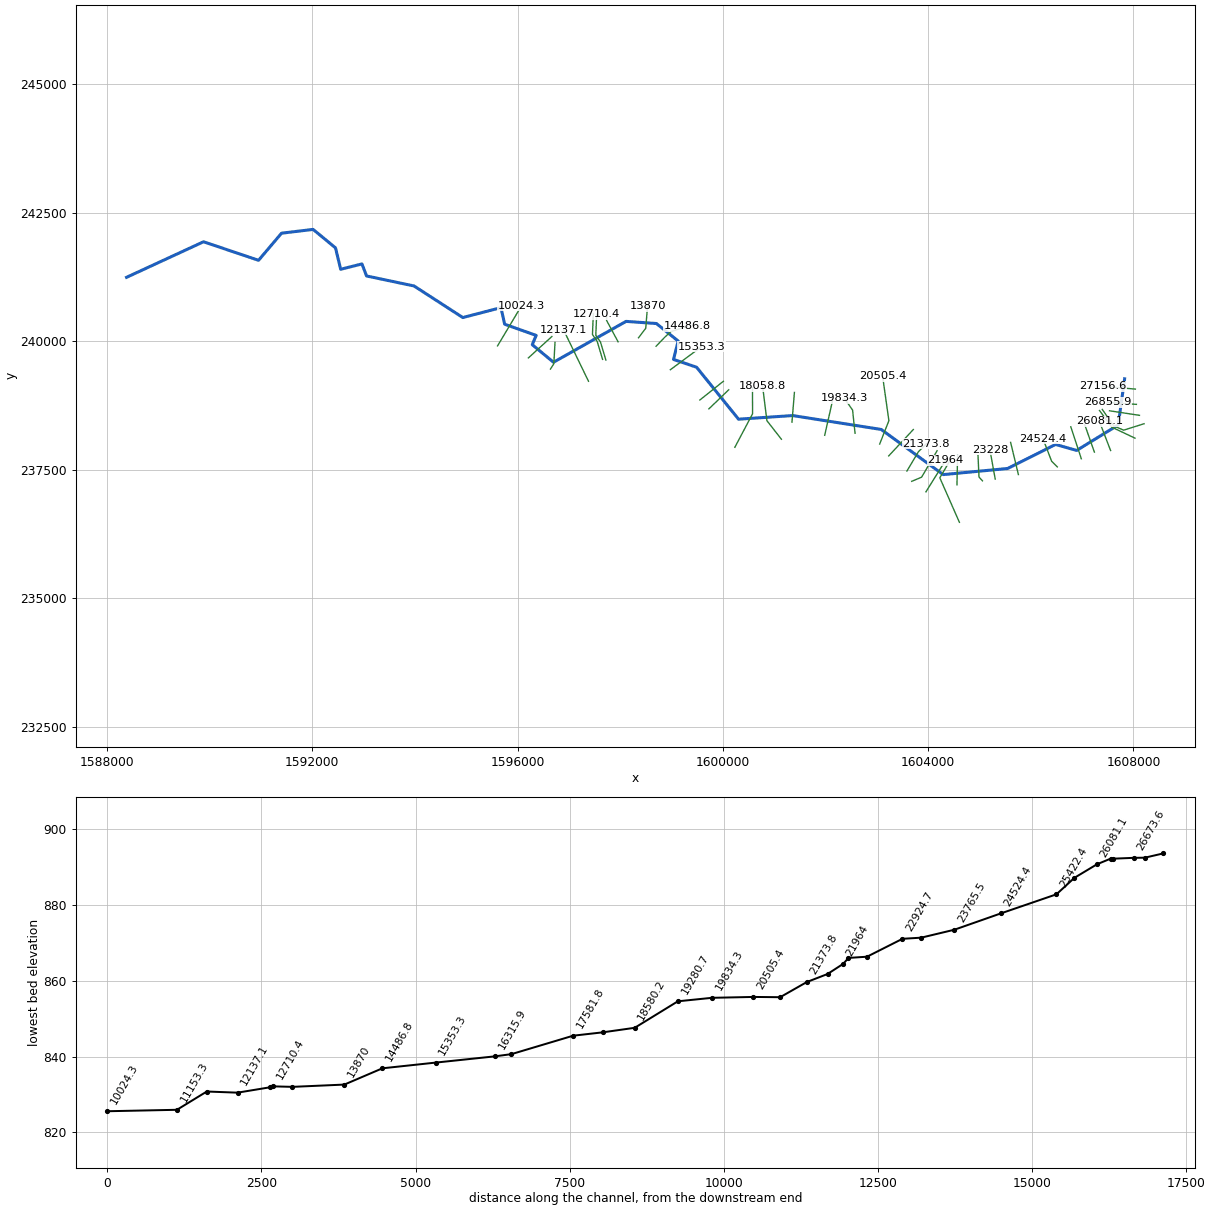
--- MIDDLEFRK.prj (project) ---

Proj Title=MIDDLEFRK
Current Plan=p01
Geom File=g01
Flow File=f01
Plan File=p01
DSS Export Rating Curves=0
DSS Export Rating Curve Sorted=0
DSS Export Volume Flow Curves=0
DXF OffsetX=0
DXF OffsetY=0
DXF ScaleX=0
DXF ScaleY=0

--- MIDDLEFRK.p01 (plan) ---

Plan Title=Floodplain
Program Version=4.00
Geom File=g01
Flow File=f01
K Sum by GR=0
Std Step Tol=0.01
Critical Tol=0.01
Num of Std Step Trials=20
Max Error Tol=0.3
Flow Tol Ratio=0.001
Split Flow NTrial=30
Split Flow Tol=0.02
Split Flow Ratio=0.02
Log Output Level=0
Friction Slope Method=1
Unsteady Friction Slope Method=2
Unsteady Bridges Friction Slope Method=1
Global Log Level=0
CheckData=False
Run HTab=0
Run UNet=0
Run PostProcess=0
UNET Theta=0
UNET Theta Warmup=0
UNET ZTol=0
UNET ZSATol=0
UNET MxIter=0
UNET MaxInSteps=0
UNET DtIC=0
UNET DtMin=0
UNET MaxCRTS=0
UNET WFStab=0
UNET SFStab=0
UNET WFX=0
UNET SFX=0
UNET DSS MLevel=0
UNET DZMax Abort=0
UNET Convert EG Bridges=0
UNET Use Existing IB Tables=0
UNET Froude Limit=0
UNET Froude Power=0
Write IC File=0
Echo Input=False
Echo Output=False
Write Detailed=0

--- MIDDLEFRK.f01 (steady flow) ---

Flow Title=NFF Regression Equation
Program Version=4.10
Number of Profiles= 1
Profile Names=P100yr
River Rch & RM=MIDDLEFRK,Main            ,27156.6
554.9325
River Rch & RM=MIDDLEFRK,Main            ,26346.7
614.6957
River Rch & RM=MIDDLEFRK,Main            ,25714.4
831.6305
River Rch & RM=MIDDLEFRK,Main            ,24524.4
842.1297
River Rch & RM=MIDDLEFRK,Main            ,22048.7
932.1297
River Rch & RM=MIDDLEFRK,Main            ,21709.6
1080.432
River Rch & RM=MIDDLEFRK,Main            ,20940.3
1097.598
River Rch & RM=MIDDLEFRK,Main            ,19834.3
1212.209
River Rch & RM=MIDDLEFRK,Main            ,19280.7
1413.878
River Rch & RM=MIDDLEFRK,Main            ,18058.8
1457.121
River Rch & RM=MIDDLEFRK,Main            ,17581.8
1647.383
River Rch & RM=MIDDLEFRK,Main            ,15353.3
  1674.3
River Rch & RM=MIDDLEFRK,Main            ,9525.9
1858.549
River Rch & RM=MIDDLEFRK,Main            ,8993.7
2101.576
River Rch & RM=MIDDLEFRK,Main            ,4045.3
2204.479
River Rch & RM=MIDDLEFRK,Main            ,3620.8
2718.128
River Rch & RM=MIDDLEFRK,Main            ,2749.3
2957.157
River Rch & RM=MIDDLEFRK,Main            ,115.8
3061.691
Boundary for River Rch & Prof#=MIDDLEFRK,Main            , 1
Up Type= 0
Dn Type= 1
Dn Known WS=816
DSS Import GetInterval= 0
DSS Import GetPeak= 0
DSS Import FillOption= 0

--- MIDDLEFRK.g01 (geometry) ---

Geom Title=USGS 10m DEM
Program Version=4.10

River Reach=MIDDLEFRK       ,Main
Reach XY= 30
     1607829.287      239271.767     1607704.864       238373.49
      1606895.02      237877.553     1606484.882      237994.252
      1605548.76      237525.623     1604294.376      237407.053
     1603086.216      238285.873     1601361.074      238556.054
     1600306.529      238485.526     1599488.821      239497.244
     1599039.602      239648.286     1599130.747      240006.359
     1598706.268      240347.505     1598115.123      240389.171
      1596701.06      239593.599     1596286.998      239936.046
     1596363.603      240116.168     1595749.541      240334.137
     1595677.145      240656.532     1594934.379      240463.761
      1593984.03      241078.358      1593058.85      241273.099
     1592969.006      241507.474     1592554.944      241403.308
     1592453.381      241819.974     1592017.409      242179.263
     1591402.131      242105.652     1590954.214      241577.874
     1589882.195       241938.84     1588382.089      241246.658

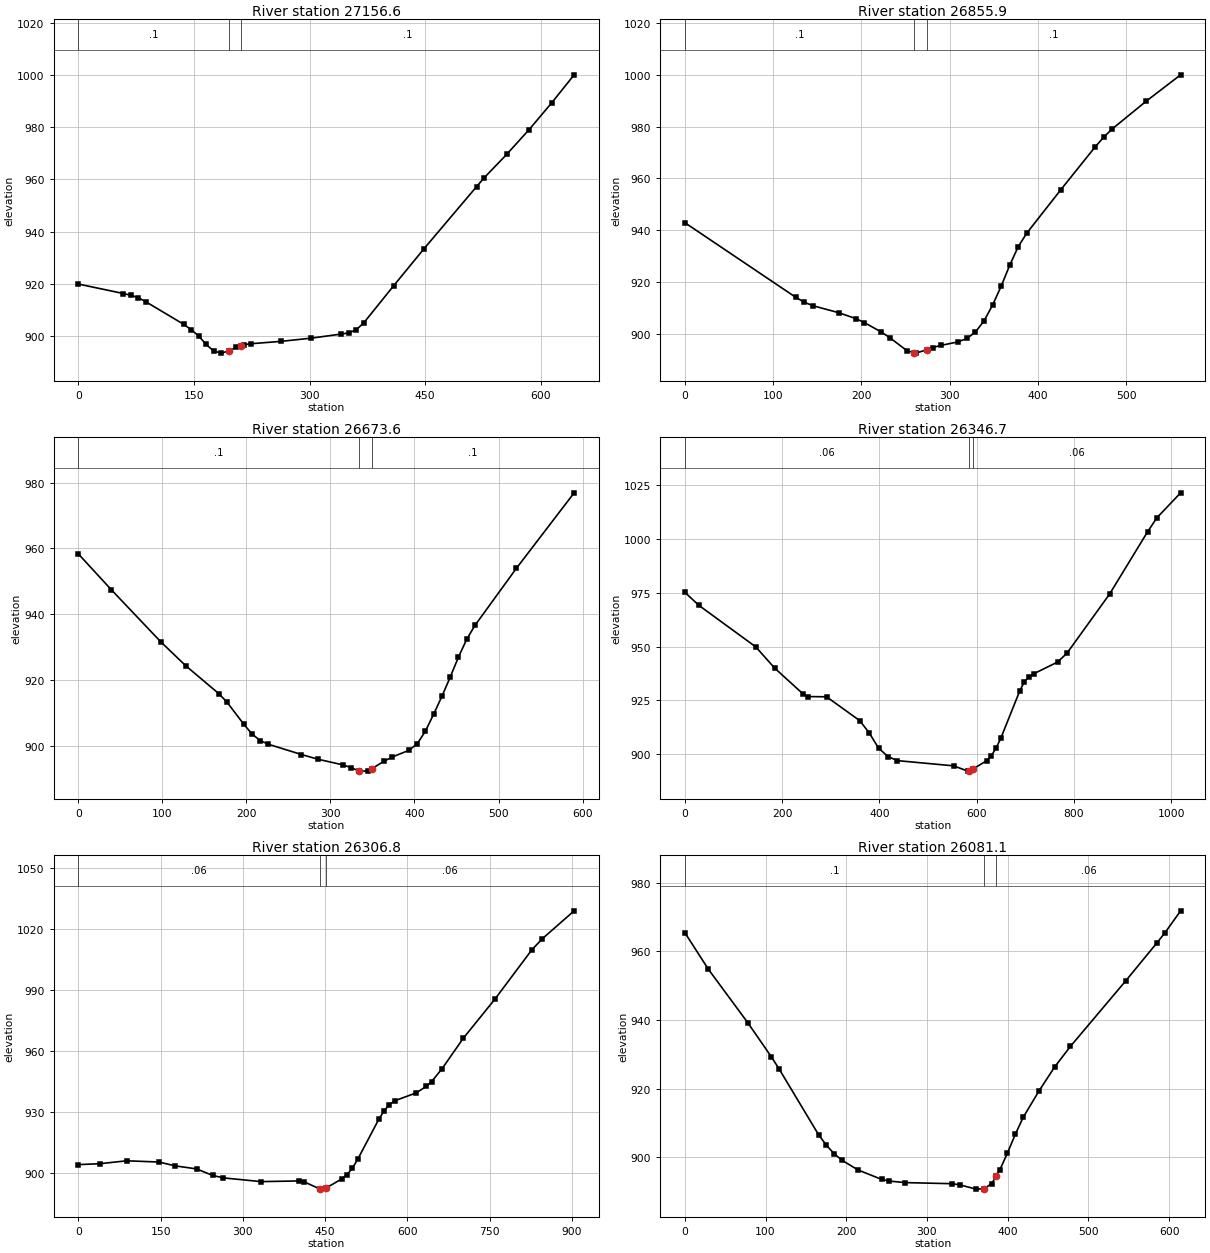
Type RM Length L Ch R = 1 ,27156.6 ,300.3,300.7,301.1
XS GIS Cut Line= 2
     1608039.029      239071.601     1607397.933      239126.269
#Sta/Elev= 30
       0     920    58.5  916.38    68.2  915.71      78  914.75    87.7  913.21
   136.5  904.64   146.2  902.61     156  900.21   165.7  896.93   175.5  894.45
   185.2  893.59   195.5  894.42   204.7  895.78   210.5  896.38   214.5   896.8
   224.2  897.19   263.2  898.09   302.2  899.32   341.2  900.88     351  901.33
   360.7  902.56   370.5   905.2   409.4  919.44   448.4  933.45   516.7  957.22
   526.4  960.56   555.7  969.54   584.9  979.04   614.2  989.27   643.4    1000
#Mann= 3 , 0 , 0
       0      .1       0   195.5    .045       0   210.5      .1       0
Bank Sta=195.5,210.5
XS Rating Curve= 0 ,0
Exp/Cntr=0.3,0.1

Type RM Length L Ch R = 1 ,26855.9 ,183.7,182.3,180.3
XS GIS Cut Line= 2
     1608058.762       238774.09     1607498.572      238811.312
#Sta/Elev= 30
       0  942.88   125.8  913.99   135.5  912.09   145.2  910.76   174.2  908.09
   193.6  905.81   203.3  904.26   222.6   900.6   232.3  898.38   251.7  893.36
   259.3  892.65   261.4  892.46   274.3  893.77   280.7  894.63   290.4  895.47
   309.8  896.84   319.4  898.15   329.1  900.61   338.8  904.92   348.5  911.02
   358.2  918.32   367.8  926.35   377.5   933.6   387.2  938.82   425.9  955.67
   464.6  972.13   474.3   975.9     484  979.11   522.7  989.89   561.4    1000
#Mann= 3 , 0 , 0
       0      .1       0   259.3    .045       0   274.3      .1       0
Bank Sta=259.3,274.3
XS Rating Curve= 0 ,0
Exp/Cntr=0.3,0.1

Type RM Length L Ch R = 1 ,26673.6 ,335.1,326.9,317.9
XS GIS Cut Line= 2
     1608118.658      238560.548     1607535.324       238649.09
#Sta/Elev= 30
       0  958.35    39.3  947.46    98.3  931.61   127.8   924.4   167.2  915.93
     177  913.32   196.7  906.71   206.5  903.73   216.3  901.71   226.2  900.57
   265.5  897.46   285.2  896.03   314.7  894.32   324.5  893.49   334.1  892.46
   344.2  892.42   349.1  893.12   363.8  895.45   373.7  896.72   393.3  898.73
   403.2  900.71     413  904.55   422.8   909.7   432.7  915.16   442.5  920.94
   452.3  927.02   462.2  932.45     472  936.66   521.2  953.95     590  976.88
#Mann= 3 , 0 , 0
       0      .1       0   334.1    .045       0   349.1      .1       0
Bank Sta=334.1,349.1
XS Rating Curve= 0 ,0
Exp/Cntr=0.3,0.1

Type RM Length L Ch R = 1 ,26346.7 ,40.9,39.9,43.7
XS GIS Cut Line= 4
     1608208.993      238397.266      1607810.42      238271.951
     1607615.243      238355.599     1607393.888      238675.912
#Sta/Elev= 30
       0  975.17    29.2  969.05   145.8  949.86   184.6  940.03   242.9  928.05
   252.6  926.79   291.5  926.68   359.5  915.65   378.9  910.04   398.4  902.88
   417.8  898.96   437.1  897.07   552.9  894.65   581.9   892.2   584.6  892.43
   591.6  893.02   620.5  897.02   630.2  899.29   639.9  902.84   649.6  907.37
   688.6  929.35   698.3  933.72     708  936.07   717.8   937.4   766.4  942.78
   785.9  946.92   873.5  974.35   951.4 1003.16   970.8 1009.74  1019.5 1021.29
#Mann= 3 , 0 , 0
       0     .06       0   584.6    .045       0   591.6     .06       0
Bank Sta=584.6,591.6
XS Rating Curve= 0 ,0
Exp/Cntr=0.3,0.1

Type RM Length L Ch R = 1 ,26306.8 ,243.4,225.7,203.3
XS GIS Cut Line= 3
     1608032.539      238116.018     1607580.641      238329.552
     1607340.012      238654.298
#Sta/Elev= 30
       0  904.26    39.2  904.71    88.2  906.14     147  905.53   176.4  903.66
   215.6  902.16     245  898.95   264.6  897.75   333.2  895.92   401.8  896.26
   411.6  895.84     441  892.24   450.8  892.66   480.2  897.23     490  899.34
   499.8  902.54   509.4   906.9   547.9  926.54   557.6   930.7   567.2  933.72
   576.8  935.58   615.3  939.38   634.5  942.65   644.2  945.02   663.4  951.41
   701.9  966.27   759.6  985.47     827 1009.69   846.2 1015.14     904 1028.77
#Mann= 3 , 0 , 0
       0     .06       0     441    .045       0   450.8     .06       0
Bank Sta=441,450.8
XS Rating Curve= 0 ,0
Exp/Cntr=0.3,0.1

Type RM Length L Ch R = 1 ,26081.1 ,358.1,366.7,412.7
XS GIS Cut Line= 2
     1607556.158      237875.653     1607334.803      238448.569
#Sta/Elev= 30
       0   965.5    29.2   954.8      78  939.23   107.2   929.3     117  925.68
   165.7  906.59   175.5  903.48   185.2  901.01     195   899.1   214.5  896.33
   243.7  893.58   253.5  893.07     273  892.63   331.5  892.31   341.2  891.95
   360.7  890.73   370.8  890.86   380.2  892.34   385.8  894.55     390   896.2
   399.7  901.27   409.5  906.75   419.2  911.66   438.7  919.32   458.2  926.35
   477.7  932.33     546  951.37   584.9  962.51   594.7  965.41   614.2  971.83
#Mann= 3 , 0 , 0
       0      .1       0   370.8    .045       0   385.8     .06       0
Bank Sta=370.8,385.8
XS Rating Curve= 0 ,0
Exp/Cntr=0.3,0.1

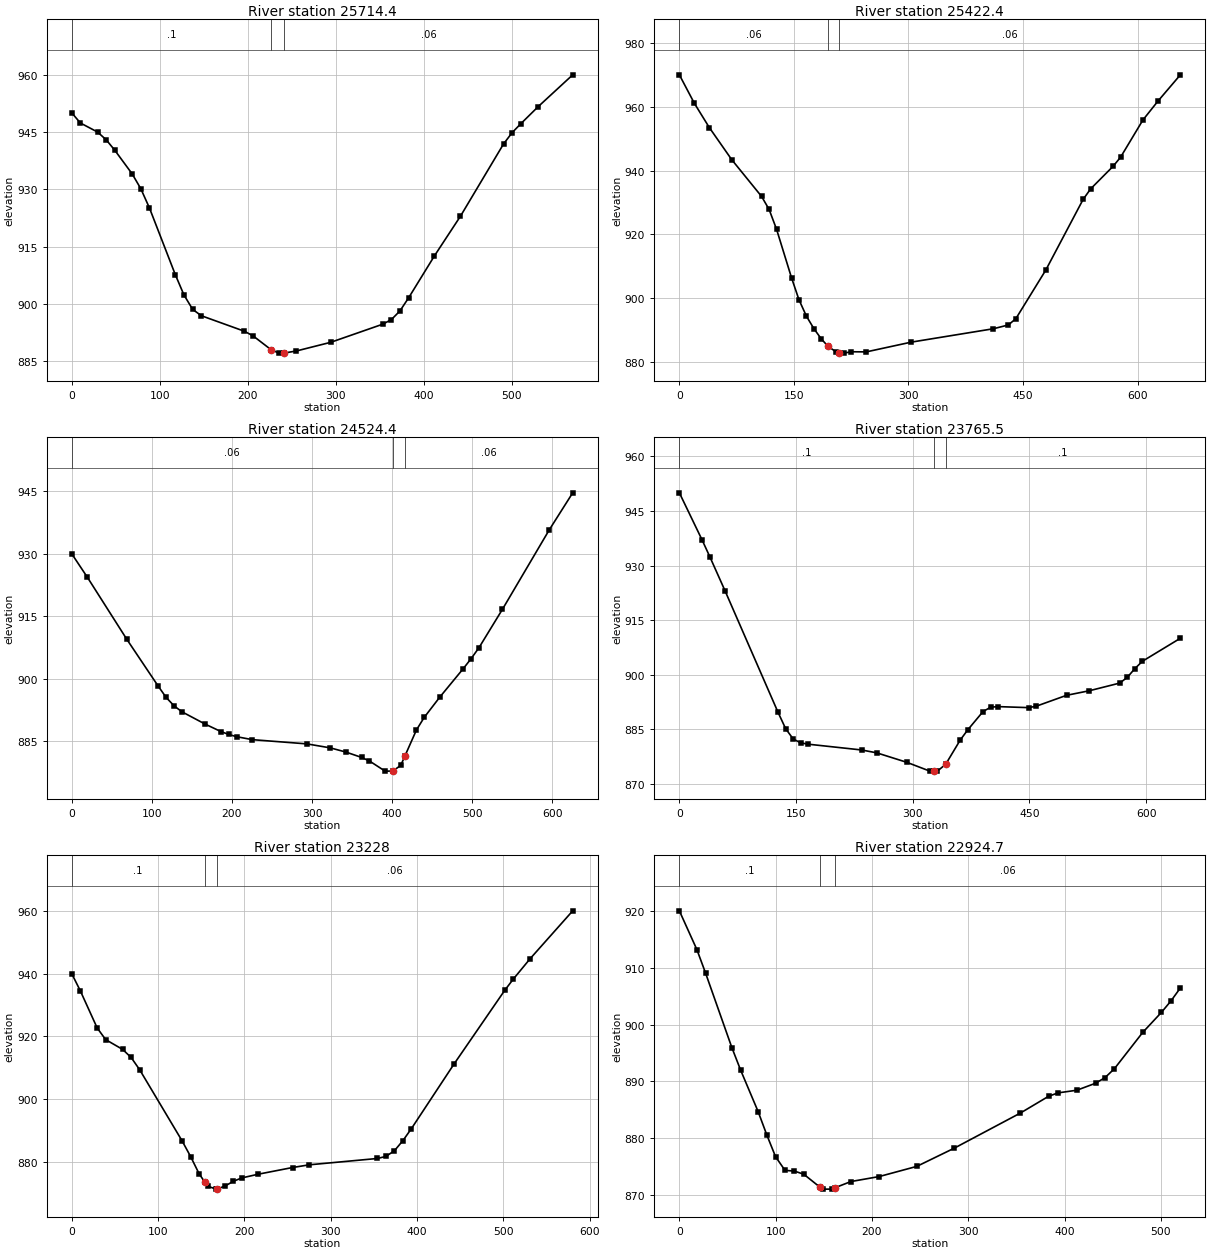
Type RM Length L Ch R = 1 ,25714.4 ,293.2,292,290.7
XS GIS Cut Line= 2
     1607240.255      237845.217     1607051.156      238381.879
#Sta/Elev= 30
       0  950.05     9.8  947.38    29.4     945    39.2  942.97      49  940.22
    68.7  934.04    78.5  930.16    88.3  925.13   117.7  907.66   127.5  902.36
   137.4  898.59   147.2  896.94   196.2  892.87     206  891.66   226.4  888.05
   235.4  887.15   241.4  887.18   255.1  887.71   294.3  889.99   353.2  894.72
     363  895.91   372.8   898.2   382.6  901.61     412  912.62   441.5  922.98
   490.5  941.91   500.3  944.88   510.1  947.19   529.8  951.66     569  959.98
#Mann= 3 , 0 , 0
       0      .1       0   226.4    .045       0   241.4     .06       0
Bank Sta=226.4,241.4
XS Rating Curve= 0 ,0
Exp/Cntr=0.3,0.1

Type RM Length L Ch R = 1 ,25422.4 ,886.8,898,893.9
XS GIS Cut Line= 2
     1606985.893      237714.239     1606780.752      238337.327
#Sta/Elev= 30
       0     970    19.6  961.09    39.2  953.48    68.5  943.44   107.7  931.88
   117.5  927.82   127.3  921.58   146.9  906.38   156.6  899.53   166.4  894.36
   176.2  890.45     186  887.21   194.6  884.95   205.6  883.11   209.6  882.98
   215.4   882.8   225.2  883.23   244.8  883.19   303.5  886.24   411.2  890.44
   430.8  891.63   440.6   893.6   479.8  908.83   528.7  930.98   538.5  934.26
   567.9  941.34   577.7  944.18     607  955.86   626.6  961.75     656     970
#Mann= 3 , 0 , 0
       0     .06       0   194.6    .045       0   209.6     .06       0
Bank Sta=194.6,209.6
XS Rating Curve= 0 ,0
Exp/Cntr=0.3,0.1

Type RM Length L Ch R = 1 ,24524.4 ,760.2,758.8,752.3
XS GIS Cut Line= 3
     1606517.993      237556.791     1606406.927      237667.858
     1606238.449      238104.819
#Sta/Elev= 30
       0     930    19.6  924.33    68.7  909.47     108  898.19   117.8  895.51
   127.6   893.5   137.4  892.06   166.8  889.06   186.3  887.29   196.1  886.59
   205.8  886.06   225.4  885.35   293.7  884.33   322.9  883.37   342.4  882.36
     362  881.07   371.7  880.22   391.2  877.79   400.7   877.8   410.7  879.16
   415.7  881.32   430.3  887.67     440  890.69   459.5  895.57   488.8  902.41
   498.6  904.81   508.3  907.41   537.6  916.63   596.1  935.73   625.4  944.63
#Mann= 3 , 0 , 0
       0     .06       0   400.7    .045       0   415.7     .06       0
Bank Sta=400.7,415.7
XS Rating Curve= 0 ,0
Exp/Cntr=0.3,0.1

Type RM Length L Ch R = 1 ,23765.5 ,538.8,537.5,534.9
XS GIS Cut Line= 2
     1605759.708      237407.964     1605607.957      238033.858
#Sta/Elev= 30
       0  949.99    29.3  936.99      39  932.48    58.6   923.1   126.8  889.65
   136.6  885.14   146.4  882.27   156.1  881.23   165.9  880.86   234.2  879.28
   253.7  878.49   292.7  875.86     322  873.46   327.3  873.48   331.8  873.49
   342.3  875.33     361     882   370.8  884.84   390.3  889.83   400.1  891.04
   409.8   891.2   448.9  890.92   458.6   891.3   497.7  894.31   526.9  895.56
     566  897.67   575.7  899.23   585.5  901.65   595.2  903.67     644     910
#Mann= 3 , 0 , 0
       0      .1       0   327.3    .045       0   342.3      .1       0
Bank Sta=327.3,342.3
XS Rating Curve= 0 ,0
Exp/Cntr=0.3,0.1

Type RM Length L Ch R = 1 ,23228   ,305.9,303.3,300.1
XS GIS Cut Line= 2
      1605308.04      237319.912     1605204.418      237890.773
#Sta/Elev= 30
       0     940     9.8  934.62    29.5  922.69    39.3  918.99      59  915.86
    68.8   913.3    78.7  909.39   127.8  886.75   137.7  881.74   147.5  876.28
   153.8  873.74   157.3  872.33   167.2  871.37   168.8  871.52     177  872.26
   186.8  873.81   196.7  874.92   216.3  876.14   255.7  878.25   275.3  879.12
     354  881.13   363.8  881.78   373.7  883.59   383.5   886.8   393.4  890.64
   442.5  911.11   501.5  934.69   511.4  938.26     531  944.79   580.2     960
#Mann= 3 , 0 , 0
       0      .1       0   153.8    .045       0   168.8     .06       0
Bank Sta=153.8,168.8
XS Rating Curve= 0 ,0
Exp/Cntr=0.3,0.1

Type RM Length L Ch R = 1 ,22924.7 ,567.9,575.1,570.4
XS GIS Cut Line= 3
      1605059.38       237285.74     1604991.827      237359.368
     1604972.824      237779.298
#Sta/Elev= 30
       0     920    18.2  913.18    27.2  909.06    54.5  895.96    63.6     892
    81.8   884.7    90.8   880.6    99.9  876.77   109.7  874.37   119.5  874.24
   129.2  873.69   146.4  871.36   148.8  871.07   158.6  871.07   161.4   871.3
   178.1   872.4   207.5  873.28   246.6  875.07   285.7  878.29   354.1  884.44
   383.4  887.39   393.2  887.99   412.8  888.46   432.3  889.69   442.1  890.68
   451.8  892.24   481.2  898.62   500.7  902.16   510.5  904.15   520.3  906.44
#Mann= 3 , 0 , 0
       0      .1       0   146.4    .045       0   161.4     .06       0
Bank Sta=146.4,161.4
XS Rating Curve= 0 ,0
Exp/Cntr=0.3,0.1

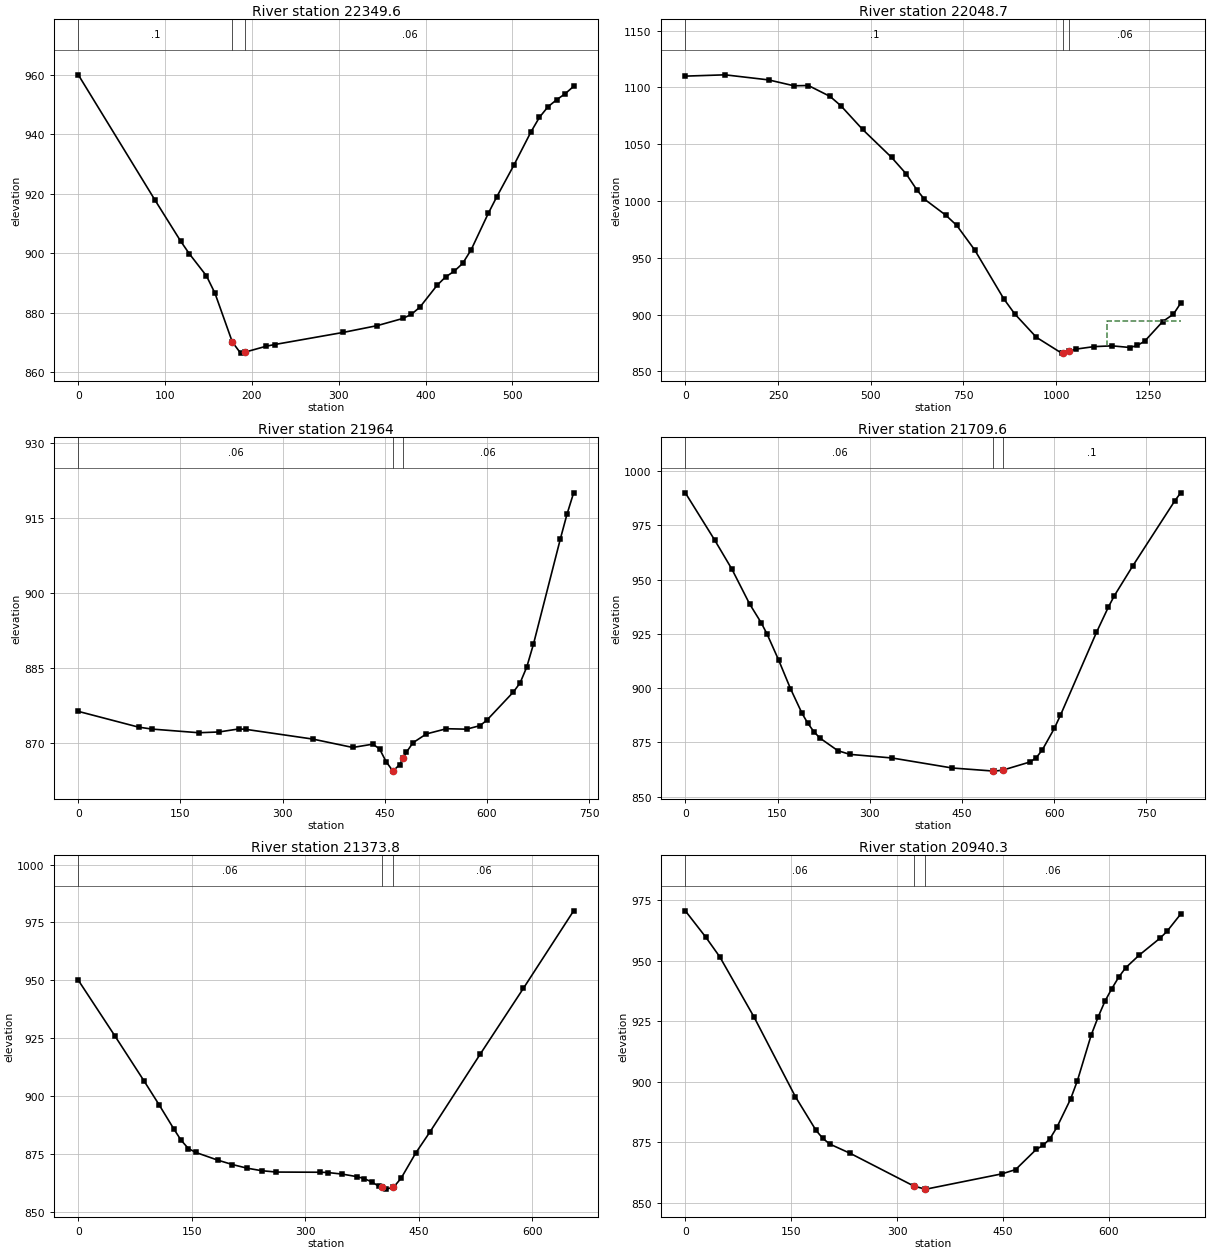
Type RM Length L Ch R = 1 ,22349.6 ,312.4,300.8,289
XS GIS Cut Line= 2
     1604562.611      237209.051     1604574.928      237779.501
#Sta/Elev= 30
       0     960    88.5  917.77     118  903.99   127.9  899.78   147.6  892.35
   157.4  886.53   177.4  870.11   186.9  866.35   192.4  866.71   216.4  868.67
   226.3  869.25     305  873.31   344.3   875.6   373.8  878.01   383.7  879.41
   393.5  881.82   413.2  889.14     423  891.97   432.9  893.88   442.7  896.52
   452.5   901.1   472.2  913.34     482  918.92   501.7  929.56   521.4  940.78
   531.2   945.7   541.1  949.26   550.9  951.58   560.8  953.63   570.6  956.12
#Mann= 3 , 0 , 0
       0      .1       0   177.4    .045       0   192.4     .06       0
Bank Sta=177.4,192.4
XS Rating Curve= 0 ,0
Exp/Cntr=0.3,0.1

Type RM Length L Ch R = 1 ,22048.7 ,85.3,84.8,84.2
XS GIS Cut Line= 3
     1604610.225      236478.663     1604228.494      237344.794
     1604426.602      237679.702
#Sta/Elev= 30
       0    1110   107.3 1111.14   224.4 1106.68   292.7  1101.5   331.8 1101.73
   390.3 1092.12   419.6 1083.85   478.1 1063.02   556.2  1038.4   595.2 1024.03
   624.5 1009.75     644 1001.82   702.6  987.44   731.8  978.54   780.6  956.75
   858.7  913.86     888  900.68   946.5     880  1014.6  866.03  1019.1  866.12
  1034.1  867.47  1053.5  869.57  1102.2  871.77  1150.8  872.44  1199.4  870.97
  1218.9  872.87  1238.4  876.47    1287  893.78  1316.2  900.36  1335.6     910
#Mann= 3 , 0 , 0
       0      .1       0  1019.1    .045       0  1034.1     .06       0
#XS Ineff= 2 , 0
                         1135.87          893.93
Permanent Ineff=
       F       F
Bank Sta=1019.1,1034.1
XS Rating Curve= 0 ,0
Exp/Cntr=0.3,0.1

Type RM Length L Ch R = 1 ,21964   ,253.6,254.4,253.4
XS GIS Cut Line= 2
     1603957.905      237071.206     1604342.964      237688.108
#Sta/Elev= 30
       0   876.4    88.4  873.26   108.1  872.87   176.9  872.14   206.4  872.29
   235.8   872.9   245.7  872.82     344  870.88   402.9   869.2   432.4  869.86
   442.2  868.92     452  866.35   461.6  864.54   461.9  864.48   471.7  865.77
   476.6     867   481.5  868.22   491.4  870.15     511   871.9   540.5  872.94
     570  872.85   589.6  873.55   599.5   874.6   638.8  880.27   648.6  882.08
   658.4  885.25   668.2  889.81   707.6  910.75   717.4  915.71   727.2     920
#Mann= 3 , 0 , 0
       0     .06       0   461.6    .045       0   476.6     .06       0
Bank Sta=461.6,476.6
XS Rating Curve= 0 ,0
Exp/Cntr=0.3,0.1

Type RM Length L Ch R = 1 ,21709.6 ,333.7,335.8,336.8
XS GIS Cut Line= 3
     1603680.866      237275.897     1603873.588      237356.743
     1604175.722      237871.528
#Sta/Elev= 30
       0     990    47.5  968.37      76  954.73   104.5  938.86   123.5  930.12
     133  924.93     152  912.86     171  899.85     190  888.35   199.5  883.75
     209  880.03   218.8  877.06   248.1  871.22   267.7  869.51   336.2  867.85
     434  863.24   501.3  861.82   502.6  861.79   516.3  862.23   561.3  866.05
     571  868.01   580.8  871.55   600.4  881.49   610.2  887.45   668.9  925.68
   688.5  937.48   698.2  942.68   727.6  956.15   796.1  986.18   805.9     990
#Mann= 3 , 0 , 0
       0     .06       0   501.3    .045       0   516.3      .1       0
Bank Sta=501.3,516.3
XS Rating Curve= 0 ,0
Exp/Cntr=0.3,0.1

Type RM Length L Ch R = 1 ,21373.8 ,437.5,433.6,428.8
XS GIS Cut Line= 3
     1603587.146      237475.864     1603810.801       237850.76
     1603964.276      238005.968
#Sta/Elev= 30
       0     950    48.5  925.85    87.3  906.25   106.7   896.2   126.1  885.79
   135.8  880.85   145.5  877.24   155.2  875.56   184.3  872.22   203.7  870.31
   223.1  868.74   242.5  867.64   261.9  867.06   320.1  866.98   329.8  866.86
   349.2  866.16   368.6  865.06   378.3  864.17     388  862.79   397.7  860.82
   401.3   860.4   407.4  859.68   416.3  860.55   417.1  860.63   426.8  864.43
     446  875.26     465  884.48   531.4  918.09   588.4   946.5   654.8     980
#Mann= 3 , 0 , 0
       0     .06       0   401.3    .045       0   416.3     .06       0
Bank Sta=401.3,416.3
XS Rating Curve= 0 ,0
Exp/Cntr=0.3,0.1

Type RM Length L Ch R = 1 ,20940.3 ,425.6,434.9,442
XS GIS Cut Line= 2
     1603233.241      237771.486     1603712.408      238284.507
#Sta/Elev= 30
       0  970.68    29.2  959.72    48.8  951.68    97.5  926.73     156  893.87
   185.2  879.97     195   876.6   204.8  874.28     234  870.42     324  856.92
     339  855.75   341.2  855.67   448.5  861.97     468  863.73   497.2  872.05
     507  873.74   516.7  876.47   526.5  881.17     546  892.88   555.7   900.5
   575.2  919.33     585  926.76   594.7  933.32   604.5  938.55   614.2  943.25
     624  947.13   643.5  952.43   672.7  959.35   682.5  962.15     702  969.31
#Mann= 3 , 0 , 0
       0     .06       0     324    .045       0     339     .06       0
Bank Sta=324,339
XS Rating Curve= 0 ,0
Exp/Cntr=0.3,0.1

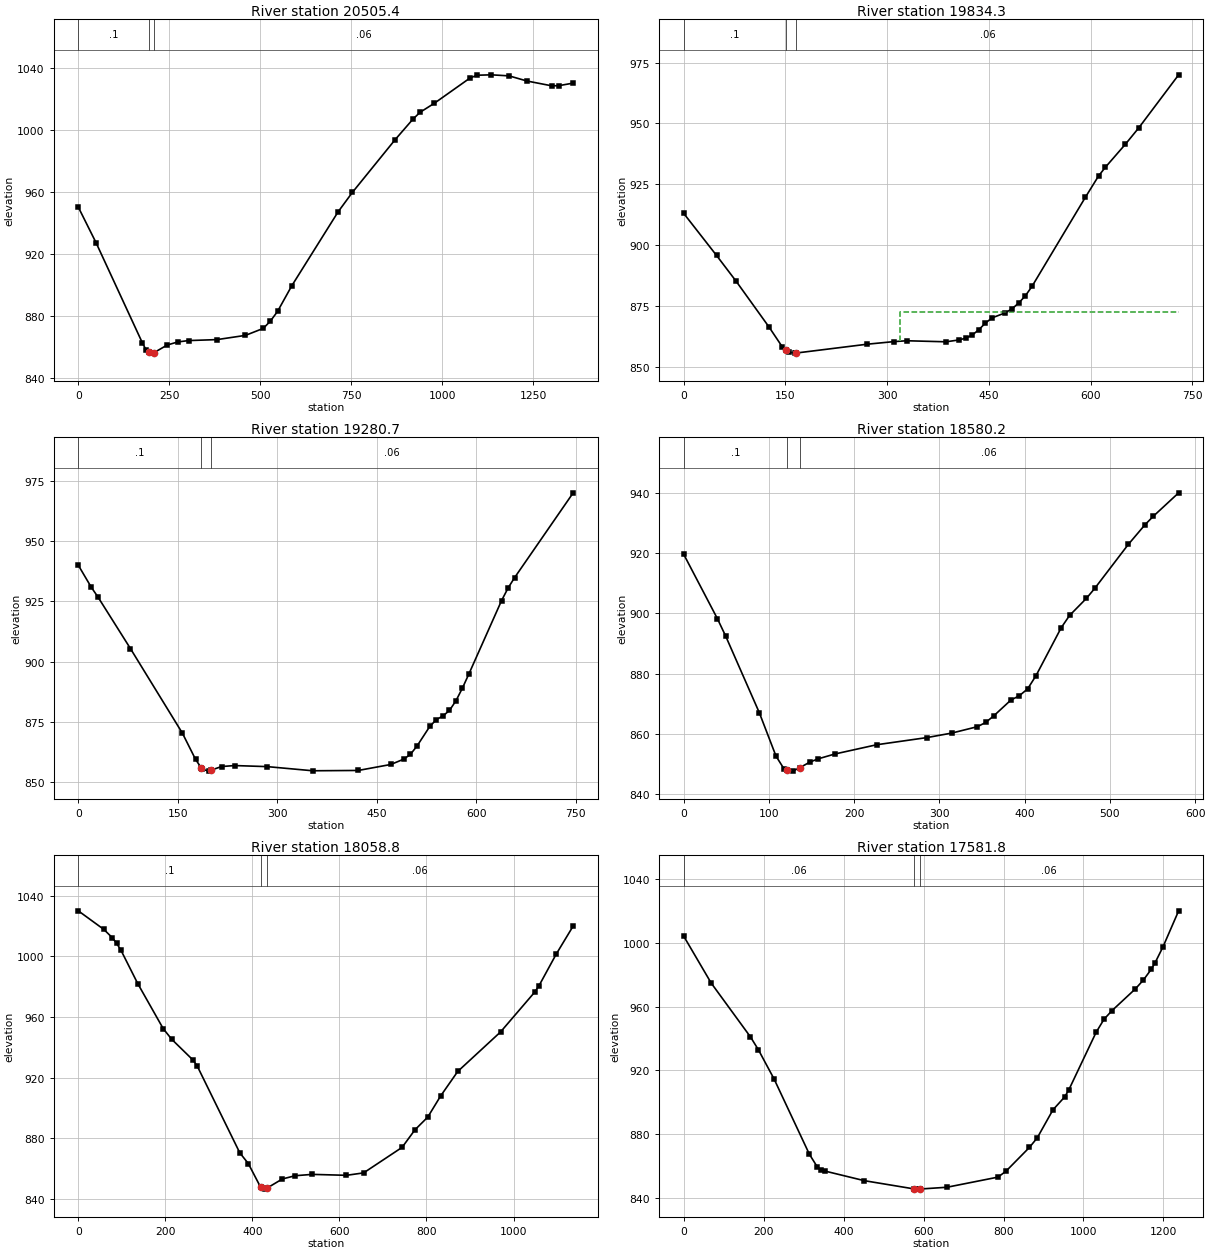
Type RM Length L Ch R = 1 ,20505.4 ,659.6,671.1,680.9
XS GIS Cut Line= 3
     1603057.173      238002.633     1603236.165      238457.212
     1603114.057      239319.344
#Sta/Elev= 30
       0  949.98    48.8     927   175.9  862.42   185.6  858.06   193.4   856.3
   205.2  855.74   208.4   856.1   244.3  860.98   273.6  862.97   302.9  863.84
   381.1  864.47   459.2   867.2   508.1  871.71   527.7  876.42   547.2  882.63
   586.4  899.21   713.6  946.92   752.7  959.43   870.1  993.46     919 1006.69
   938.6 1011.14   977.7 1016.95  1075.6 1033.23  1095.1 1035.08  1134.3 1035.34
  1183.2 1034.67  1232.1 1031.36  1300.6 1028.23  1320.2 1028.35  1359.3    1030
#Mann= 3 , 0 , 0
       0      .1       0   193.4    .045       0   208.4     .06       0
Bank Sta=193.4,208.4
XS Rating Curve= 0 ,0
Exp/Cntr=0.3,0.1

Type RM Length L Ch R = 1 ,19834.3 ,560.4,553.6,545.6
XS GIS Cut Line= 3
     1602576.991       238211.59     1602528.397      238663.676
     1602369.807      238888.749
#Sta/Elev= 30
       0  912.98    48.4  895.69    77.4  885.04   125.8  866.25   145.1   858.2
   151.2  856.77   154.8  855.93   164.5  855.51   166.2  855.56   270.9  859.19
   309.6  860.24   328.9   860.6     387  860.17   406.3  860.95     416  861.68
   425.7  862.96   435.3  865.16     445  867.87   454.7     870   474.4  872.11
   484.2  873.73     494  876.11   503.9  879.08   513.7  882.97   592.4  919.61
     612  928.44   621.9  931.96   651.4  941.43     671  948.12     730     970
#Mann= 3 , 0 , 0
       0      .1       0   151.2    .045       0   166.2     .06       0
#XS Ineff= 2 , 0
                          318.28          872.27
Permanent Ineff=
       F       F
Bank Sta=151.2,166.2
XS Rating Curve= 0 ,0
Exp/Cntr=0.3,0.1

Type RM Length L Ch R = 1 ,19280.7 ,697.2,700.5,703.2
XS GIS Cut Line= 2
     1601985.531      238171.979     1602150.012      238899.893
#Sta/Elev= 30
       0  939.99    19.6  930.84    29.5  926.86    78.6  905.43   157.1  870.28
   176.8  859.48   185.1  856.08   186.6  855.46   196.4  854.59   200.1  854.98
     216  856.49   235.7   856.9   284.8  856.46   353.5  854.74   422.2  854.87
   471.3  857.35     491  859.58   500.8  861.54   510.6  864.92   530.2  873.18
   540.1  875.97   549.9  877.47   559.7  879.75   569.5  883.76   579.3  889.04
   589.2     895   638.2  925.26   648.1  930.52   657.9  934.82   746.3     970
#Mann= 3 , 0 , 0
       0      .1       0   185.1    .045       0   200.1     .06       0
Bank Sta=185.1,200.1
XS Rating Curve= 0 ,0
Exp/Cntr=0.3,0.1

Type RM Length L Ch R = 1 ,18580.2 ,503.8,521.3,538.4
XS GIS Cut Line= 2
     1601347.824      238427.736     1601395.409      239006.453
#Sta/Elev= 30
       0  919.57    39.4  898.27    49.2  892.44    88.6  867.05   108.3  852.56
   118.1  848.15   121.3  847.97   127.9   847.6   136.3  848.75   147.6  850.55
   157.5  851.66   177.2  853.28   226.4  856.36   285.4  858.74   314.9  860.26
   344.5  862.35   354.3  863.75   364.2  866.06   383.8  871.18   393.7  872.62
   403.5   874.9   413.4  879.33   442.9  895.21   452.7  899.28   472.4  904.94
   482.2  908.25   521.6  922.86   541.3  929.43   551.1  932.25   580.7     940
#Mann= 3 , 0 , 0
       0      .1       0   121.3    .045       0   136.3     .06       0
Bank Sta=121.3,136.3
XS Rating Curve= 0 ,0
Exp/Cntr=0.3,0.1

Type RM Length L Ch R = 1 ,18058.8 ,500.1,477,449.1
XS GIS Cut Line= 3
     1601141.875      238095.185     1600859.403      238456.981
     1600775.338      239129.874
#Sta/Elev= 30
       0 1030.01    58.6 1017.76    78.1 1012.31    87.9 1008.64    97.7  1004.2
   136.7  981.95   195.3  952.21   214.8  945.22   263.7  931.53   273.4  927.54
   371.1  870.34   390.6  863.29     419  847.62   429.7   846.4     434  847.14
   468.8  853.09   498.3  855.25   537.6  856.13   616.2  855.51   655.6  857.12
     744  873.96   773.5  885.52     803  893.94   832.5  907.85   871.8  924.03
   970.1  950.07  1048.7  976.38  1058.5  980.58  1097.8 1001.29  1137.1    1020
#Mann= 3 , 0 , 0
       0      .1       0     419    .045       0     434     .06       0
Bank Sta=419,434
XS Rating Curve= 0 ,0
Exp/Cntr=0.3,0.1

Type RM Length L Ch R = 1 ,17581.8 ,998.4,1001,992.3
XS GIS Cut Line= 3
     1600234.814      237938.828     1600579.725      238590.103
      1600578.49       239091.21
#Sta/Elev= 30
       0 1004.08    68.8  974.66     167  940.93   186.7  932.92     226  914.58
   314.4  867.36   334.1  859.46   343.9  857.58   353.8  856.81     452  850.81
   575.9  845.67   579.8  845.52   590.9  845.58   658.4  846.69   786.1  853.05
   805.8  856.67   864.7  871.64   884.4  877.68   923.7  895.25   953.1  903.36
     963  907.58  1031.7  943.86  1051.4  952.01    1071  957.34    1130   971.1
  1149.6  976.52  1169.3  983.23  1179.1  987.42  1198.8  997.33  1238.1    1020
#Mann= 3 , 0 , 0
       0     .06       0   575.9    .045       0   590.9     .06       0
Bank Sta=575.9,590.9
XS Rating Curve= 0 ,0
Exp/Cntr=0.3,0.1

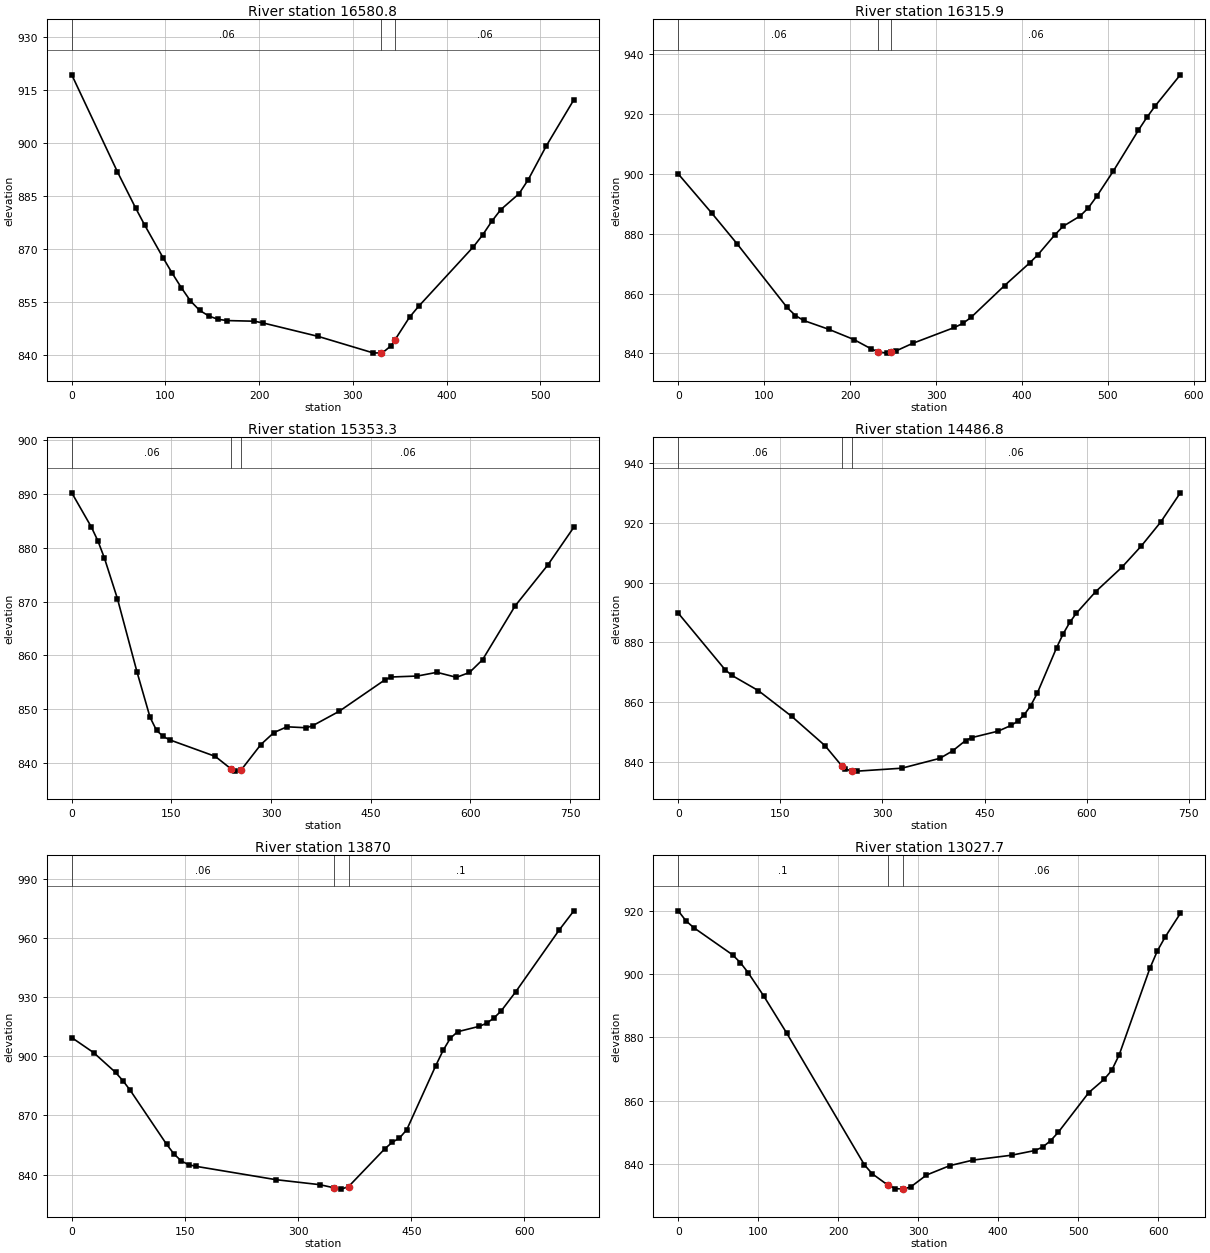
Type RM Length L Ch R = 1 ,16580.8 ,267.2,264.9,262.3
XS GIS Cut Line= 2
     1599729.283      238686.736     1600115.568       239057.83
#Sta/Elev= 30
       0   919.3    48.7   891.9    68.2  881.63    77.9  876.79    97.4  867.62
   107.1  863.26   116.9  859.15   126.6  855.42   136.4  852.75   146.1  851.17
   155.8  850.23   165.6  849.86   194.8  849.68   204.5  849.16     263  845.38
   321.4  840.74   329.8  840.67   331.1  840.66   340.9   842.8   344.8   844.4
   360.4  850.82   370.1  853.89   428.5   870.7   438.3  874.02     448  877.86
   457.7   881.2   477.2   885.7     487  889.66   506.4  899.26   535.7  912.25
#Mann= 3 , 0 , 0
       0     .06       0   329.8    .045       0   344.8     .06       0
Bank Sta=329.8,344.8
XS Rating Curve= 0 ,0
Exp/Cntr=0.3,0.1

Type RM Length L Ch R = 1 ,16315.9 ,963.7,962.6,960.1
XS GIS Cut Line= 2
     1599554.025      238859.668     1600011.148       239223.35
#Sta/Elev= 30
       0     900    38.9  886.93    68.2  876.73   126.6  855.36   136.3  852.66
     146  850.99   175.2  848.04   204.4  844.62   223.9   841.6     233  840.45
   243.4  840.08     248  840.41   253.1  840.78   272.6  843.33   321.3  848.65
     331  849.99   340.8  852.05   379.7  862.67   408.9  870.24   418.6     873
   438.1  879.59   447.8  882.48   467.3  885.86     477  888.58   486.8  892.45
   506.3  900.97   535.5  914.63   545.2  918.87   554.9   922.7   584.2  933.13
#Mann= 3 , 0 , 0
       0     .06       0     233    .045       0     248     .06       0
Bank Sta=233,248
XS Rating Curve= 0 ,0
Exp/Cntr=0.3,0.1

Type RM Length L Ch R = 1 ,15353.3 ,861.5,866.5,868.5
XS GIS Cut Line= 2
     1598978.162      239448.176     1599585.801      239897.395
#Sta/Elev= 30
       0  890.23    29.4  883.88    39.3  881.29    49.1   878.1    68.7  870.54
    98.1  856.93   117.8  848.46   127.6  846.01   137.4  844.91   147.2  844.26
   215.9  841.18   240.1  838.81   245.3  838.43   255.1  838.67   284.6  843.38
   304.2   845.6   323.8  846.68   353.3   846.5   363.1  846.92   402.4  849.56
   471.1   855.4   480.9  855.95   520.1  856.13   549.6  856.82     579  855.89
   598.6  856.79   618.3  859.17   667.3  869.18   716.4  876.78   755.7  883.83
#Mann= 3 , 0 , 0
       0     .06       0   240.1    .045       0   255.1     .06       0
Bank Sta=240.1,255.1
XS Rating Curve= 0 ,0
Exp/Cntr=0.3,0.1

Type RM Length L Ch R = 1 ,14486.8 ,600.3,616.8,621.6
XS GIS Cut Line= 4
     1598700.875      239905.822     1598863.638      240075.818
     1598986.848      240189.539     1599304.965      240293.659
#Sta/Elev= 30
       0  889.76    68.6  870.91    78.4     869   117.7  863.85   166.7  855.24
   215.7  845.43   240.6  838.61   244.7  837.63   255.6  836.98   263.3  836.92
   328.5   837.9   384.4   841.2     403  843.66   422.2  847.16   431.7  848.15
     470  850.29   489.1  852.21   498.7  853.62   508.2  855.72   517.8  858.79
   527.4  862.92     556  878.24   565.6  882.85   575.2  886.64   584.7  889.67
   613.4  896.96   651.7  905.07   680.4  912.22     709  920.25   737.7     930
#Mann= 3 , 0 , 0
       0     .06       0   240.6    .045       0   255.6     .06       0
Bank Sta=240.6,255.6
XS Rating Curve= 0 ,0
Exp/Cntr=0.3,0.1

Type RM Length L Ch R = 1 ,13870   ,827.8,842.3,854.4
XS GIS Cut Line= 3
     1598357.502      240070.138     1598498.561        240254.6
     1598533.284      240686.457
#Sta/Elev= 30
       0  909.47      29  901.85      58  891.84    67.7  887.66    77.4   882.8
   125.8  855.31   135.5  850.45   145.1  846.94   154.8  845.02   164.5   844.2
   270.7  837.42   328.5   834.9   347.8  833.29   357.4  832.63   366.9  833.93
   415.1  853.16   424.8  856.38   434.4  858.55     444  862.75   482.5  895.28
   492.2  902.99   501.8  909.17   511.4  912.45   540.3  915.22   549.9  916.76
   559.6  919.44   569.2  923.02   588.4  932.69   646.2  964.12   665.5  973.78
#Mann= 3 , 0 , 0
       0     .06       0   347.8    .045       0   366.9      .1       0
Bank Sta=347.8,366.9
XS Rating Curve= 0 ,0
Exp/Cntr=0.3,0.1

Type RM Length L Ch R = 1 ,13027.7 ,314.8,317.3,319.7
XS GIS Cut Line= 3
     1597959.256        239992.4     1597734.037      240410.883
     1597743.353      240563.194
#Sta/Elev= 30
       0     920     9.7  916.83    19.4  914.68    67.9   906.1    77.6  903.65
    87.3  900.49   106.7  893.16   135.8  881.28   232.8  839.71   242.5   836.9
   261.9  833.34   271.6  832.21   281.3  832.03     291  832.78   310.4  836.48
   339.5  839.45   368.6  841.21     417  842.76   446.1  844.24   455.8  845.34
   465.5  847.32   475.2     850   513.4  862.56   532.5  866.72     542  869.56
   551.5  874.57   589.7   901.8   599.2  907.38   608.8  911.71   627.8  919.17
#Mann= 3 , 0 , 0
       0      .1       0   261.9    .045       0   281.3     .06       0
Bank Sta=261.9,281.3
XS Rating Curve= 0 ,0
Exp/Cntr=0.3,0.1

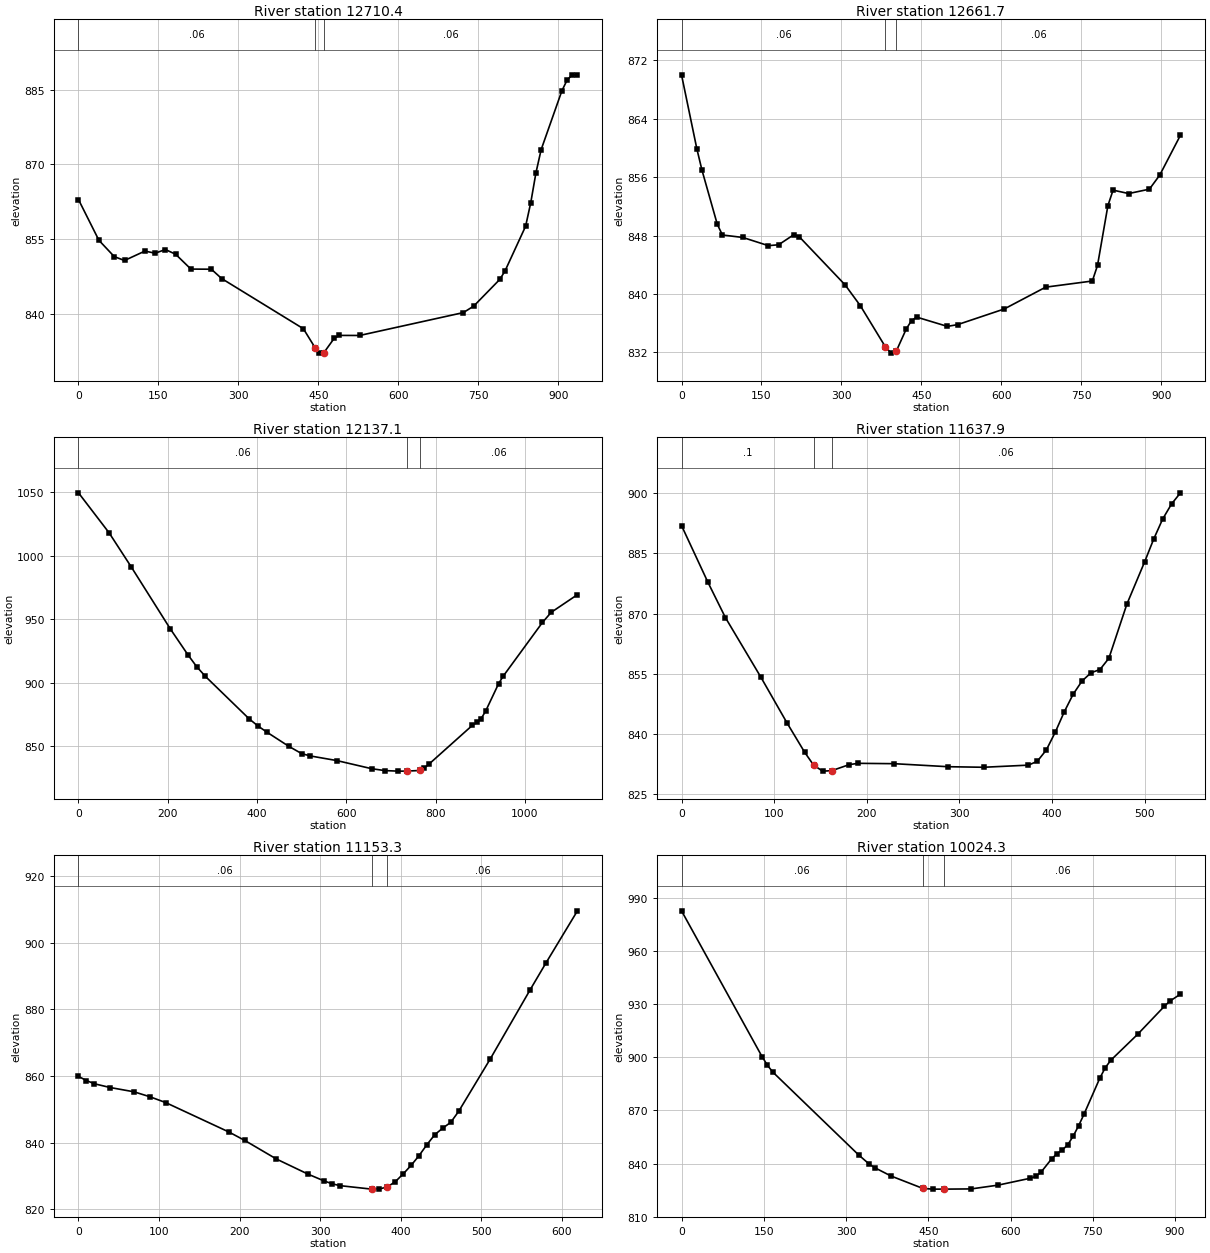
Type RM Length L Ch R = 1 ,12710.4 ,49.9,48.8,47.8
XS GIS Cut Line= 4
     1597722.479       239635.67     1597617.738      239984.479
      1597525.29      240119.028     1597542.651      240527.014
#Sta/Elev= 30
       0  862.94    38.3  854.78    67.1  851.51    86.3  850.73   124.6  852.62
   143.8  852.19   162.9  852.93   182.1  851.99   210.8  849.01   249.2  848.98
   268.4  847.12   421.8  837.05     444   833.2   450.6  832.16   460.2  832.25
   479.4   835.1     489  835.71   527.4   835.7   721.9  840.29   741.3  841.59
     790  846.92   799.7  848.57   838.6   857.6   848.3  862.35     858  868.32
   867.7  872.94   906.6  884.74   916.4   886.9   926.1  887.94   935.8  887.95
#Mann= 3 , 0 , 0
       0     .06       0     444    .045       0   460.2     .06       0
Bank Sta=444,460.2
XS Rating Curve= 0 ,0
Exp/Cntr=0.3,0.1

Type RM Length L Ch R = 1 ,12661.7 ,527.1,524.5,521.1
XS GIS Cut Line= 4
     1597657.375      239649.993     1597552.634      239998.802
     1597460.186      240133.351     1597477.547      240541.337
#Sta/Elev= 30
       0     870    28.8  859.86    38.3  856.97    67.1  849.54    76.7  848.08
     115  847.74   162.9  846.62   182.1  846.74   210.8  848.13   220.4  847.87
   306.7  841.26   335.4   838.4   382.1   832.8     393  831.91   402.6  832.15
   421.8  835.26   431.4  836.36     441  836.84   498.6  835.57   517.8  835.81
   605.2  837.95     683  840.94   770.5  841.78   780.2  843.91   799.7   852.1
   809.4  854.22   838.6  853.75   877.5  854.35   896.9  856.27   935.8  861.74
#Mann= 3 , 0 , 0
       0     .06       0   382.1    .045       0   402.6     .06       0
Bank Sta=382.1,402.6
XS Rating Curve= 0 ,0
Exp/Cntr=0.3,0.1

Type RM Length L Ch R = 1 ,12137.1 ,510.8,499.3,487.3
XS GIS Cut Line= 2
     1597383.252       239223.55     1596894.829      240228.992
#Sta/Elev= 30
       0 1049.64    68.6 1018.14   117.7  991.57   205.9   942.4   245.1  922.13
   264.7  912.79   284.4  905.07   382.4  871.65     402  866.07   421.6   861.3
   470.6  850.15   500.1  844.26   519.7  842.43   578.5  838.83     657   832.4
   686.4  830.92   715.8   830.5   735.4   830.5   764.8  831.02   774.6  832.89
   784.4  835.76   882.5  866.59   892.3  868.84   902.1  871.88   911.9   877.6
   941.3  899.44   951.1  905.08  1039.4  947.56    1059  955.53  1117.8  969.46
#Mann= 3 , 0 , 0
       0     .06       0   735.4    .045       0   764.8     .06       0
Bank Sta=735.4,764.8
XS Rating Curve= 0 ,0
Exp/Cntr=0.3,0.1

Type RM Length L Ch R = 1 ,11637.9 ,501.2,484.6,467.1
XS GIS Cut Line= 3
     1596641.922      239461.046     1596707.894      239565.213
     1596730.463      239980.143
#Sta/Elev= 30
       0  891.87    28.4  877.82    47.4  868.98    85.4  854.28   113.8  842.84
     133  835.48   142.6  832.31   152.3   830.8     162   830.9   181.3  832.43
     191  832.74   229.6  832.65   287.6   831.9   326.2  831.76   374.6  832.29
   384.2  833.25   393.9  836.05   403.6  840.48   413.2  845.49   422.9  849.92
   432.5  853.21   442.2  855.26   451.9  856.07   461.5  858.87   480.9  872.31
   500.2   882.9   509.8  888.46   519.5  893.46   529.2  897.25   538.8  900.01
#Mann= 3 , 0 , 0
       0      .1       0   142.6    .045       0     162     .06       0
Bank Sta=142.6,162
XS Rating Curve= 0 ,0
Exp/Cntr=0.3,0.1

Type RM Length L Ch R = 1 ,11153.3 ,1119.7,1129,1136.1
XS GIS Cut Line= 2
     1596211.366       239678.06     1596669.699      240094.727
#Sta/Elev= 30
       0  859.87     9.8  858.64    19.7  857.66    39.3  856.53    68.8  855.25
    88.5  853.77   108.2  852.01   186.8  843.15   206.5  840.61   245.8  835.02
   285.1  830.47   304.8  828.46   314.6   827.6   324.5  827.03   363.8  825.98
   373.6  826.03   383.4  826.64   393.3  828.22   403.1  830.56     413  833.14
   422.8  836.06   432.6  839.37   442.4  842.38   452.3  844.34   462.1  846.06
   471.9  849.34   511.3  865.18   560.4   885.8   580.1   893.9   619.4  909.66
#Mann= 3 , 0 , 0
       0     .06       0   363.8    .045       0   383.4     .06       0
Bank Sta=363.8,383.4
XS Rating Curve= 0 ,0
Exp/Cntr=0.3,0.1

Type RM Length L Ch R = 1 ,10024.3 ,495.7,498.4,498.1
XS GIS Cut Line= 2
     1595610.845      239912.632     1596078.242      240693.247
#Sta/Elev= 30
       0   982.5   146.8  900.33   156.5  895.49   166.3  891.64   322.8  844.93
   342.4  839.69   352.2  837.71   381.6  833.05   440.2  825.98   458.2   825.6
   479.4   825.6   528.3  825.72   577.2  827.85   635.9  831.73   645.7  832.78
   655.5  835.14     675  842.72   684.8  845.64   694.6   847.7   704.4  850.67
   714.2  855.49     724  861.27   733.8  867.77   763.1  888.42   772.9  894.15
   782.7  898.24   831.6  912.85   880.5   928.7   890.3  931.55   909.8  935.54
#Mann= 3 , 0 , 0
       0     .06       0   440.2    .045       0   479.4     .06       0
Bank Sta=440.2,479.4
XS Rating Curve= 0 ,0
Exp/Cntr=0.3,0.1