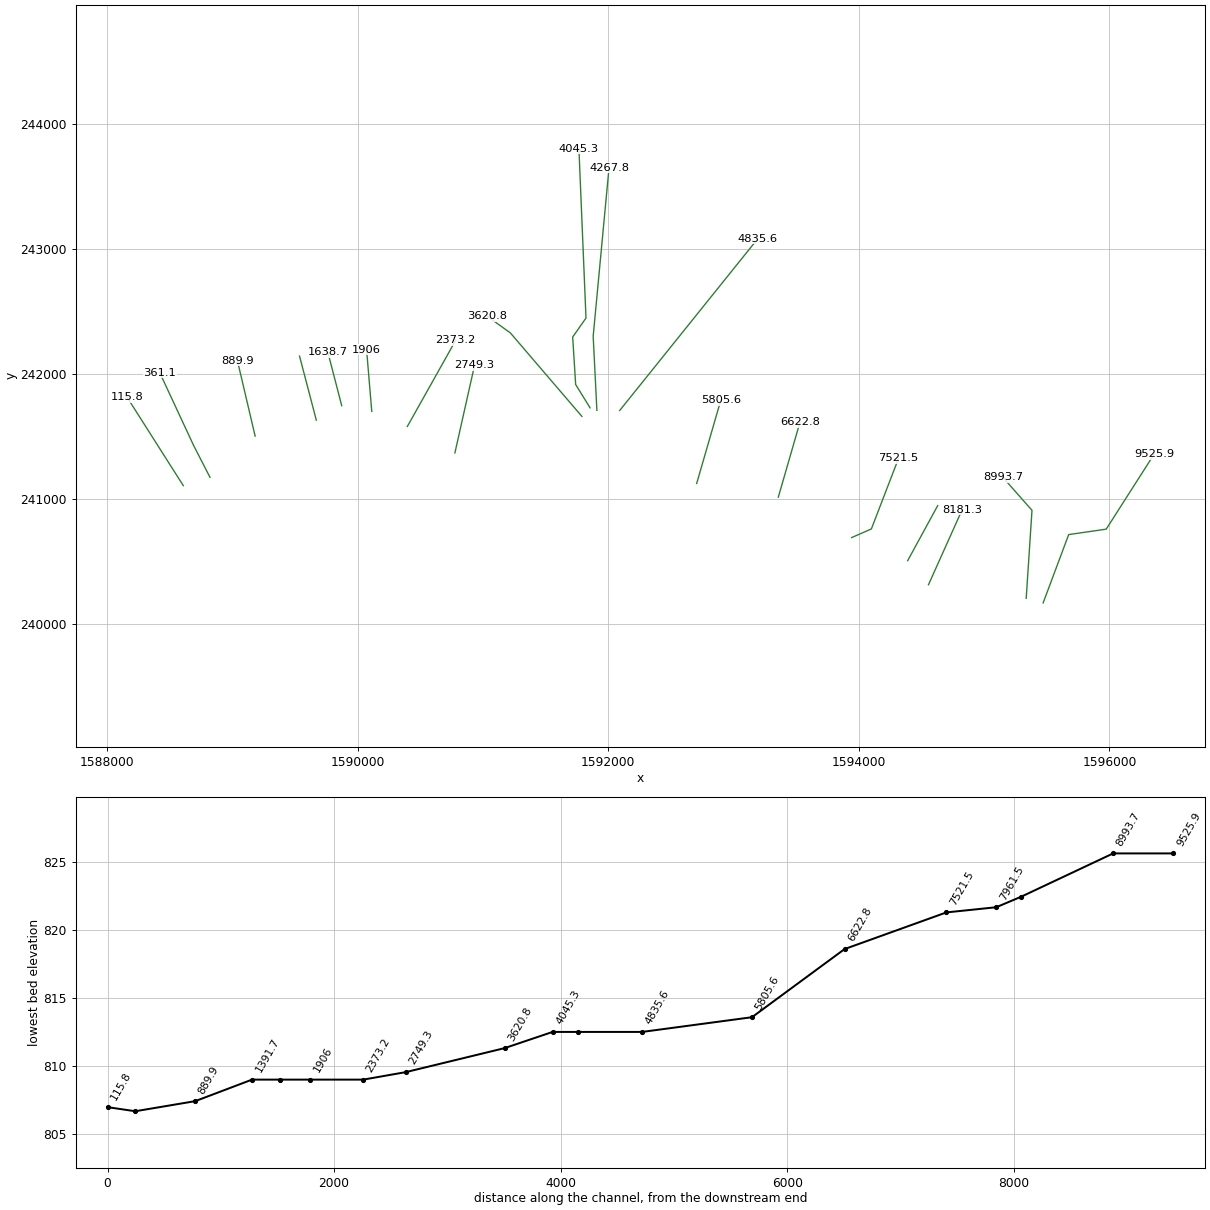
HEC-RAS study MIDDLEFRK.prj: MIDDLEFRK

--- MIDDLEFRK.g01 (geometry) --- (continued)

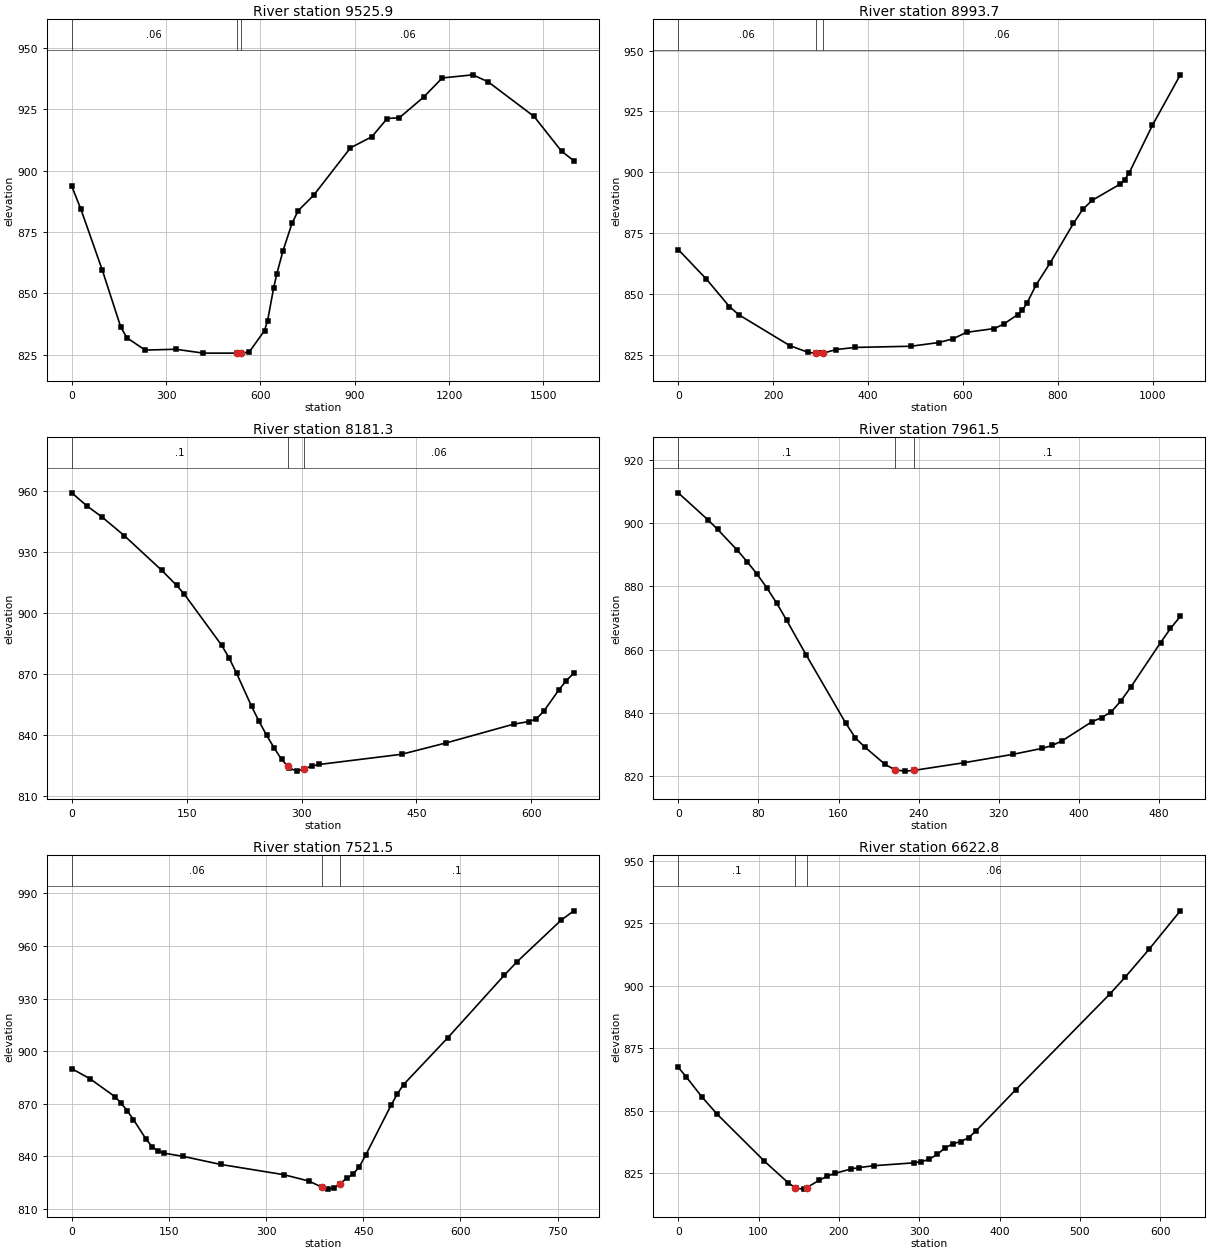
Type RM Length L Ch R = 1 ,9525.9  ,523.8,532.3,538.5
XS GIS Cut Line= 4
     1595470.603      240168.073     1595674.596      240714.948
     1595974.075      240758.351      1596356.02      241357.309
#Sta/Elev= 30
       0  893.61    29.2  884.17    97.3  859.35   155.6   836.3   175.1  831.86
   233.5  826.84   330.8  827.18   418.3   825.6   524.6   825.6   539.6   825.6
   564.2  826.04     613  834.79   622.7  838.83   642.2  852.25     652  857.88
   671.5  867.19   700.8  878.65   720.3  883.68   769.2  889.93   886.3  909.27
   954.4  913.79  1003.1  921.21    1042  921.54  1119.8  930.04  1178.2  937.74
  1275.5  939.02  1324.2  936.16  1470.2  922.05  1557.7  907.87  1596.7  904.02
#Mann= 3 , 0 , 0
       0     .06       0   524.6    .045       0   539.6     .06       0
Bank Sta=524.6,539.6
XS Rating Curve= 0 ,0
Exp/Cntr=0.3,0.1

Type RM Length L Ch R = 1 ,8993.7  ,820.2,812.4,803.5
XS GIS Cut Line= 3
     1595335.512      240205.197     1595381.703      240908.999
     1595148.803      241173.488
#Sta/Elev= 30
       0  868.18    58.8  856.14   107.8  844.75   127.4   841.4   235.1  828.68
   274.3  825.87   290.9  825.61   293.9   825.6   305.9  825.65   333.1  827.08
   372.2  827.94   489.8  828.43   548.6  829.94     578  831.43   607.4  834.15
   666.1  835.71   685.7  837.56   715.1  841.42   724.9  843.19   734.7  846.18
   754.3  853.77   783.6  862.72   832.6  878.93   852.2  884.71   871.7  888.37
   930.5  895.03   940.3  896.74     950  899.74     999  919.28  1057.7     940
#Mann= 3 , 0 , 0
       0     .06       0   290.9    .045       0   305.9     .06       0
Bank Sta=290.9,305.9
XS Rating Curve= 0 ,0
Exp/Cntr=0.3,0.1

Type RM Length L Ch R = 1 ,8181.3  ,221.2,219.8,217.8
XS GIS Cut Line= 2
     1594555.619       240314.02     1594823.567      240912.387
#Sta/Elev= 30
       0  958.96    19.6  952.58    39.1  947.22    68.5  937.98   117.4  920.97
     137  913.53   146.8  909.32   195.7  884.18   205.5  877.91   215.3  870.34
   234.8  854.21   244.6  846.79   254.4  840.06   264.2  833.82     274  828.17
   281.8  824.87   283.8  824.03   293.6  822.42   303.4  823.57   313.1  824.87
   322.9  825.68   430.6  830.68   489.3  836.31   577.3  845.49   596.9  846.73
   606.7  848.08   616.5  851.88     636  862.26   645.8  866.87   655.6   870.5
#Mann= 3 , 0 , 0
       0      .1       0   281.8    .045       0   303.4     .06       0
Bank Sta=281.8,303.4
XS Rating Curve= 0 ,0
Exp/Cntr=0.3,0.1

Type RM Length L Ch R = 1 ,7961.5  ,436.5,440,443
XS GIS Cut Line= 2
     1594389.491      240506.382     1594629.074      240946.486
#Sta/Elev= 30
       0  909.51    29.5  901.03    39.3  897.98      59  891.38    68.8  887.75
    78.6  883.88    88.4  879.53    98.2  874.73   108.1  869.33   127.7  858.32
     167   836.9   176.9  832.08   186.7  829.12   206.3  823.82   216.2  822.06
     226  821.65   235.8  821.91   284.9  824.29   334.1  826.95   363.5  828.86
   373.4  829.76   383.2  831.23   412.7  837.21   422.5  838.54   432.3   840.4
   442.1  843.94     452  848.33   481.4  862.24   491.3  866.68   501.1  870.51
#Mann= 3 , 0 , 0
       0      .1       0   216.2    .045       0   235.8      .1       0
Bank Sta=216.2,235.8
XS Rating Curve= 0 ,0
Exp/Cntr=0.3,0.1

Type RM Length L Ch R = 1 ,7521.5  ,896.5,898.7,898.5
XS GIS Cut Line= 3
     1593942.686       240691.21     1594099.636      240760.107
     1594316.179      241323.669
#Sta/Elev= 30
       0     890    28.6  884.12    66.7     874    76.2  870.34    85.7  865.88
    95.2  860.94   114.3  849.97   123.8  845.54   133.3  842.94   142.8  841.75
   171.4     840   229.8  835.36   327.2  829.52   366.2  825.87   385.6  822.45
   395.4  821.27   405.1  821.93   414.4  824.42   424.6  827.55   434.3  829.79
   444.1  834.15   453.8  840.71   492.8  869.05   502.5  875.57   512.2  880.92
   580.4  907.59     668  943.42   687.5  951.02   755.7  974.78   775.1  980.03
#Mann= 3 , 0 , 0
       0     .06       0   385.6    .045       0   414.4      .1       0
Bank Sta=385.6,414.4
XS Rating Curve= 0 ,0
Exp/Cntr=0.3,0.1

Type RM Length L Ch R = 1 ,6622.8  ,817.4,817.2,816.1
XS GIS Cut Line= 2
     1593356.888      241014.427     1593530.044      241615.109
#Sta/Elev= 30
       0  867.35     9.8  863.58    29.3  855.57    48.8  848.46   107.4  829.74
   136.8  821.14   145.2  819.23   146.5  818.94   156.3  818.58   160.2  819.23
   175.8  822.19   185.6  823.74   195.4  824.93   214.9  826.61   224.7   827.2
   244.2  827.97     293   829.1   302.8  829.57   312.6  830.52   322.3   832.5
   332.1  835.03   341.9  836.76   351.6   837.6   361.4  839.13   371.2  842.04
     420  858.28   537.2  896.64   556.8  903.57   586.1  914.57   625.1     930
#Mann= 3 , 0 , 0
       0      .1       0   145.2    .045       0   160.2     .06       0
Bank Sta=145.2,160.2
XS Rating Curve= 0 ,0
Exp/Cntr=0.3,0.1

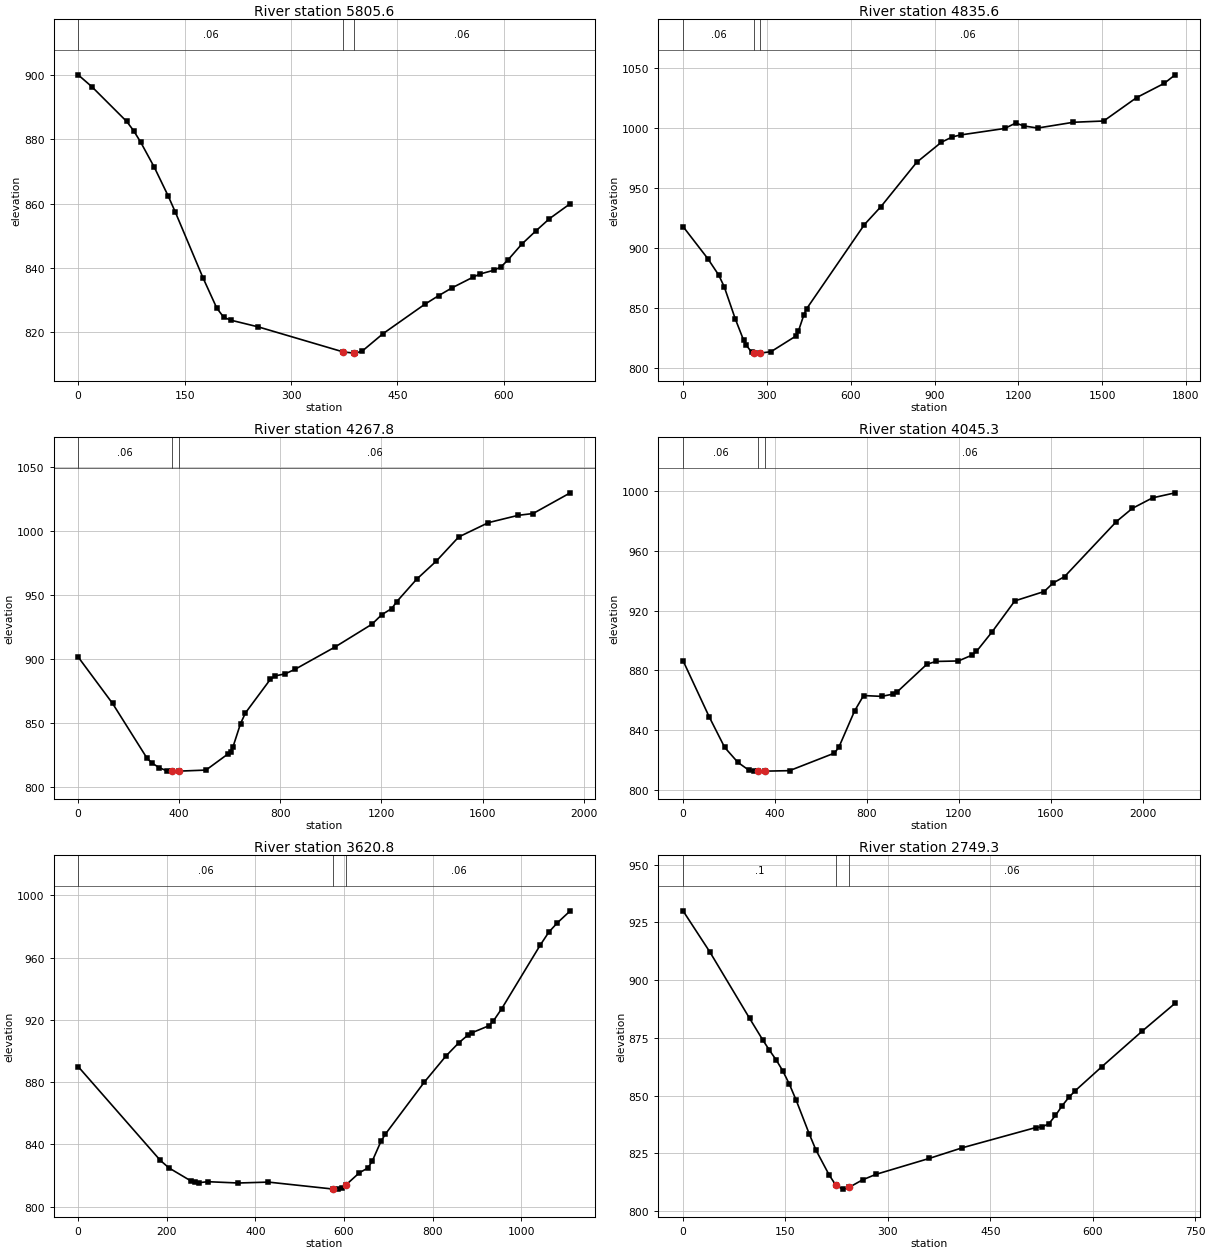
Type RM Length L Ch R = 1 ,5805.6  ,981.8,970,957.7
XS GIS Cut Line= 2
     1592705.209      241123.637     1592897.821      241789.962
#Sta/Elev= 30
       0     900    19.5  896.27    68.4  885.52    78.2  882.65    87.9  879.18
   107.5  871.23     127  862.33   136.8  857.45   175.8  837.04   195.4  827.56
   205.2   824.7   214.9  823.83     254  821.72   373.5  813.96   388.5  813.59
   390.8  813.58   400.5  814.24   429.8  819.64   488.4  828.73     508  831.42
   527.5  833.92   556.8   837.2   566.6  838.16   586.2  839.34   595.9  840.35
   605.7   842.5   625.2  847.42   644.8  851.47   664.3  855.34   693.6     860
#Mann= 3 , 0 , 0
       0     .06       0   373.5    .045       0   388.5     .06       0
Bank Sta=373.5,388.5
XS Rating Curve= 0 ,0
Exp/Cntr=0.3,0.1

Type RM Length L Ch R = 1 ,4835.6  ,555.4,567.8,577.8
XS GIS Cut Line= 2
     1592090.829       241707.57     1593192.769      243081.497
#Sta/Elev= 30
       0  918.14    88.6  891.37   127.9  877.58   147.6   867.8     187  841.08
   216.5  823.49   226.3  819.17     246  813.08   255.8   812.5   275.5   812.5
   314.9   813.7   403.4  826.68   413.2  831.06   432.9  844.72   442.8  849.68
   649.4  919.82   708.4  934.75   836.3  971.73   924.9  988.51   964.2  992.94
   993.8  994.56  1151.2  999.95  1190.6 1004.46  1220.1 1002.04  1269.3 1000.31
  1397.2 1005.13  1505.4 1006.18  1623.5 1025.74  1721.9 1037.57  1761.2 1044.71
#Mann= 3 , 0 , 0
       0     .06       0   255.8    .045       0   275.5     .06       0
Bank Sta=255.8,275.5
XS Rating Curve= 0 ,0
Exp/Cntr=0.3,0.1

Type RM Length L Ch R = 1 ,4267.8  ,188.6,222.5,256.3
XS GIS Cut Line= 3
     1591908.805      241708.856     1591879.171       242301.43
      1592005.76      243649.331
#Sta/Elev= 30
       0   901.7   136.2   865.4   272.3  822.66   291.8  818.82     321   815.2
   350.2  812.78   369.6   812.5   399.4   812.5   505.8  813.32   593.3  825.99
   603.1  827.64   612.9  831.61   642.4  849.56     662  858.02   760.1  884.15
   779.7  886.92     819  888.53   858.2  892.08  1015.2  909.37  1162.3   927.3
  1201.6   934.8  1240.8  939.58  1260.4  944.92  1338.9  962.39  1417.4  976.71
  1505.7  995.51  1623.4 1006.71  1741.1 1012.41    1800 1013.83  1947.2    1030
#Mann= 3 , 0 , 0
       0     .06       0   369.6    .045       0   399.4     .06       0
Bank Sta=369.6,399.4
XS Rating Curve= 0 ,0
Exp/Cntr=0.3,0.1

Type RM Length L Ch R = 1 ,4045.3  ,433.3,424.5,414.5
XS GIS Cut Line= 5
     1591854.378      241728.786     1591739.361      241915.418
     1591715.489      242295.192     1591821.826      242447.102
     1591765.402      243801.269
#Sta/Elev= 30
       0  886.54   114.4  848.71   181.1  828.42   238.7  818.36   287.5     813
     307   812.5   326.6   812.5   357.6   812.5   463.2  812.81   658.3  824.56
   677.8   828.5   746.1  852.78   785.2  863.13   863.8  862.59   912.9  864.08
   932.5  865.74  1060.2  884.06  1099.5  885.98  1197.7  886.31  1256.6  890.19
  1276.2  892.68    1345  905.94  1443.2  926.56  1570.9  932.84  1610.2  938.61
  1659.3  942.79  1885.2  979.73  1953.9  988.51  2042.3   995.6  2140.5  998.96
#Mann= 3 , 0 , 0
       0     .06       0   326.6    .045       0   357.6     .06       0
Bank Sta=326.6,357.6
XS Rating Curve= 0 ,0
Exp/Cntr=0.3,0.1

Type RM Length L Ch R = 1 ,3620.8  ,893.5,871.4,848.9
XS GIS Cut Line= 3
     1591789.227      241660.206     1591218.368      242328.052
     1591030.384       242463.82
#Sta/Elev= 30
       0     890   185.5  829.74     205  824.91   253.8  816.68   263.6  815.69
   273.3  815.48   292.9  816.08   361.2  815.24   429.5  815.82     576  811.33
   585.7  811.31   595.5  812.15   605.2  814.24   634.5   821.8     654  824.92
   663.8   829.4   683.3     842   693.1  846.56     781  879.96   829.8  896.73
     859  905.28   878.6     910   888.2  911.66   926.9   916.2   936.6  919.12
   955.9  927.21  1042.8  968.02  1062.2  976.36  1081.5  982.32  1110.5  989.98
#Mann= 3 , 0 , 0
       0     .06       0     576    .045       0   605.2     .06       0
Bank Sta=576,605.2
XS Rating Curve= 0 ,0
Exp/Cntr=0.3,0.1

Type RM Length L Ch R = 1 ,2749.3  ,382.6,376.1,369.5
XS GIS Cut Line= 2
      1590775.46      241368.365     1590932.938      242071.804
#Sta/Elev= 30
       0     930      39  912.34    97.4  883.52   116.9  874.07   126.6  869.66
   136.4  865.48   146.1  860.76   155.9  854.88   165.6  848.13   185.1  833.28
   194.8   826.4   214.3  815.54   223.4  811.46     224  811.19   233.8  809.55
   243.5  810.36     263  813.57   282.5  815.94   360.4  822.82   409.1  827.45
   516.3  836.17     526  836.48   535.8  837.85   545.5  841.42   555.2  845.59
     565  849.23   574.7  852.21   613.7  862.61   672.1  877.82   720.8     890
#Mann= 3 , 0 , 0
       0      .1       0   223.4    .045       0   243.5     .06       0
Bank Sta=223.4,243.5
XS Rating Curve= 0 ,0
Exp/Cntr=0.3,0.1

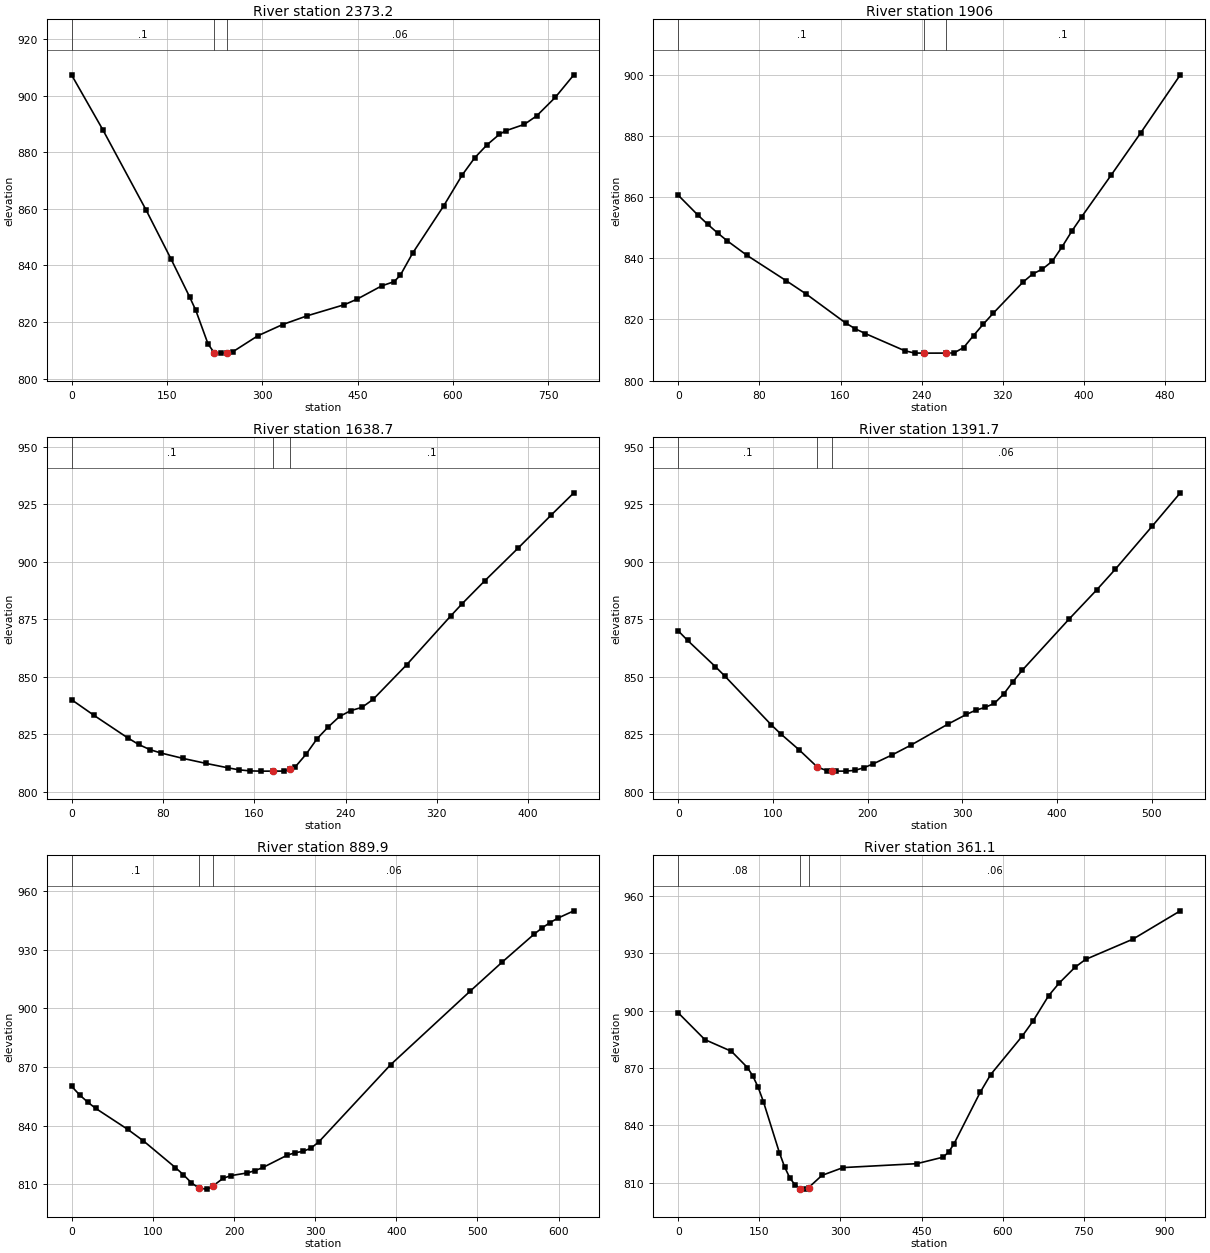
Type RM Length L Ch R = 1 ,2373.2  ,453.4,467.2,481
XS GIS Cut Line= 2
      1590396.12      241580.185     1590782.124      242269.695
#Sta/Elev= 30
       0  907.21    48.8  887.98   117.1  859.53   156.1  842.32   185.4  828.91
   195.1  824.18   214.6  812.16   224.4  809.09   234.1     809   243.9  809.03
   253.6   809.5   292.7  815.11   331.7  819.09   370.7  822.21   429.2  826.13
   448.8  828.05   487.8  832.77   507.3  834.26     517   836.5   536.6  844.38
   585.3  861.03   614.6     872   634.1  878.02   653.6  882.64   673.1  886.35
   682.9  887.59   712.2  889.85   731.7  892.86   760.9  899.38   790.2  907.37
#Mann= 3 , 0 , 0
       0      .1       0   224.4    .045       0   243.9     .06       0
Bank Sta=224.4,243.9
XS Rating Curve= 0 ,0
Exp/Cntr=0.3,0.1

Type RM Length L Ch R = 1 ,1906    ,263.5,267.3,271.1
XS GIS Cut Line= 2
      1590111.93      241700.175     1590070.585      242193.319
#Sta/Elev= 30
       0  860.63    19.4  854.13    29.1  851.11    38.8  848.28    48.5  845.67
    67.9  840.94   106.7  832.62   126.1  828.33     165  818.86   174.7  816.92
   184.4   815.4   223.2  809.79   232.9  809.03   242.6     809     264  809.01
   271.7  809.04   281.4  810.84   291.1  814.76   300.8  818.51   310.5  822.05
   339.6  832.15   349.3  834.86     359  836.49   368.7  839.05   378.4  843.78
   388.1  848.96   397.8  853.65     427  867.33   456.1  881.14   494.9     900
#Mann= 3 , 0 , 0
       0      .1       0   242.6    .045       0     264      .1       0
Bank Sta=242.6,264
XS Rating Curve= 0 ,0
Exp/Cntr=0.3,0.1

Type RM Length L Ch R = 1 ,1638.7  ,247,247,247
XS GIS Cut Line= 2
     1589871.931      241746.319     1589761.693      242172.512
#Sta/Elev= 30
       0     840    19.6  833.21    48.9  823.51    58.7  820.58    68.5  818.35
    78.3  816.86    97.8   814.5   117.4  812.39     137  810.43   146.7  809.56
   156.5  809.09   166.3     809   176.1     809   185.9  809.02   191.4  809.94
   195.6  810.64   205.4  816.33   215.2  823.16     225  828.28   234.8  832.76
   244.6   835.3   254.4  836.72   264.1  840.15   293.5  855.18   332.6  876.66
   342.4  881.86     362   891.7   391.3  905.95   420.6  920.47   440.2     930
#Mann= 3 , 0 , 0
       0      .1       0   176.1    .045       0   191.4      .1       0
Bank Sta=176.1,191.4
XS Rating Curve= 0 ,0
Exp/Cntr=0.3,0.1

Type RM Length L Ch R = 1 ,1391.7  ,502.3,501.7,501.2
XS GIS Cut Line= 2
     1589669.374      241629.976     1589535.317      242142.703
#Sta/Elev= 30
       0  869.98     9.8  865.87    39.3  854.39    49.1  850.37    98.1  829.17
     108  825.27   127.6  818.26   146.8  810.78     157  809.19   161.8   809.1
   166.8     809   176.6     809   186.5  809.33   196.3  810.52   206.1  812.22
   225.7  816.03   245.4  820.25   284.6  829.41   304.2  833.66     314  835.48
   323.9  836.71   333.7  838.46   343.5  842.48   353.3  847.86   363.1  852.84
   412.2  874.94   441.6  887.74   461.3  896.74   500.5  915.59     530     930
#Mann= 3 , 0 , 0
       0      .1       0   146.8    .045       0   161.8     .06       0
Bank Sta=146.8,161.8
XS Rating Curve= 0 ,0
Exp/Cntr=0.3,0.1

Type RM Length L Ch R = 1 ,889.9   ,523.2,528.9,533.9
XS GIS Cut Line= 2
     1589180.991      241502.536     1589039.838      242105.156
#Sta/Elev= 30
       0     860     9.8  855.64    19.6  852.01    29.5  848.79    68.8  838.09
    88.4  832.11   127.7  818.47   137.5  814.84   147.4  810.69   157.2  807.81
     167  807.42   174.7  809.26   186.7     813   196.5  814.36   216.1   815.7
     226  816.91   235.8  818.54   265.3  824.75   275.1  826.06   284.9  826.77
   294.7  828.34   304.6  831.65     393  871.15   491.2  908.89   530.5  923.71
   569.8     938   579.6  941.19   589.5  943.96   599.3  946.27   618.9     950
#Mann= 3 , 0 , 0
       0      .1       0   157.2    .045       0   174.7     .06       0
Bank Sta=157.2,174.7
XS Rating Curve= 0 ,0
Exp/Cntr=0.3,0.1

Type RM Length L Ch R = 1 ,361.1   ,243.4,245.3,247.4
XS GIS Cut Line= 3
     1588820.481      241173.202     1588690.272      241427.109
     1588419.466      242010.245
#Sta/Elev= 30
       0  898.78    49.2   884.8    98.4  878.68   127.9  870.21   137.8  865.86
   147.6     860   157.4  852.45     187  825.77   196.8  818.18   206.6  812.37
   216.5  808.74     226     807   236.2  806.68     241  807.47   265.7  813.86
   304.8  817.94   441.2  819.98   489.9   823.4   499.7  826.03   509.4  830.09
   558.1  857.17   577.6  866.51     636  886.62   655.5  894.28   684.8  907.72
   704.2   914.3   733.5  922.57     753  926.67   840.6  937.27   928.3  952.08
#Mann= 3 , 0 , 0
       0     .08       0     226    .045       0     241     .06       0
Bank Sta=226,241
XS Rating Curve= 0 ,0
Exp/Cntr=0.3,0.1

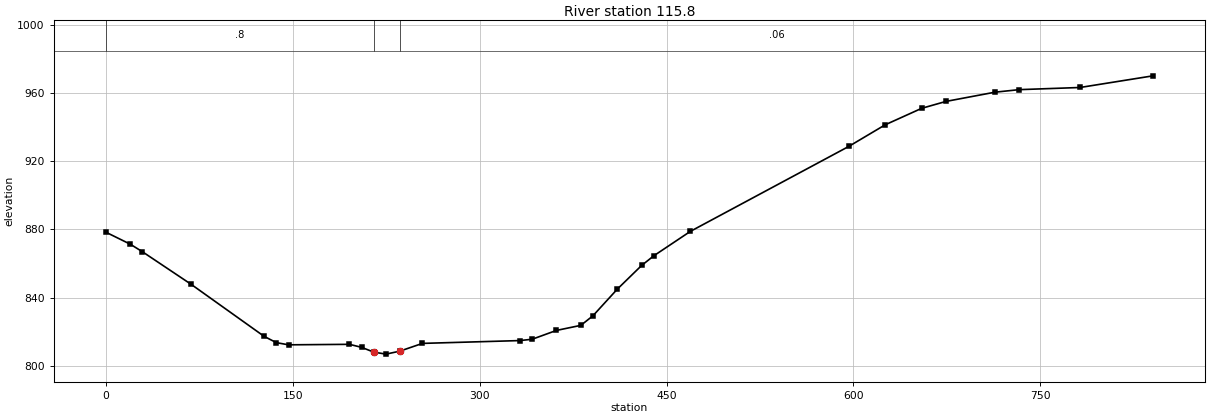
Type RM Length L Ch R = 1 ,115.8   ,117.8,115.8,113.7
XS GIS Cut Line= 2
      1588607.66      241106.314     1588157.381      241816.042
#Sta/Elev= 30
       0   878.4    19.6  871.36    29.3  866.96    68.4  847.88     127  817.39
   136.8  813.71   146.6  812.43   195.5  812.72   205.2  810.96     215  808.16
   224.8  806.98   235.8   808.7   254.1  813.27   332.3  814.92   342.1  815.69
   361.6  820.86   381.2  823.83   390.9  829.42   410.5  845.06     430  858.92
   439.8  864.59   469.1  878.87   596.2  928.62   625.5  941.31   654.8  950.97
   674.4  955.03   713.5   960.4     733   961.9   781.9  963.17   840.5     970
#Mann= 3 , 0 , 0
       0      .8       0     215    .045       0   235.8     .06       0
Bank Sta=215,235.8
XS Rating Curve= 0 ,0
Exp/Cntr=0.3,0.1

Chan Stop Cuts=-1
Use User Specified Reach Order=0
Composite Channel Slope=5